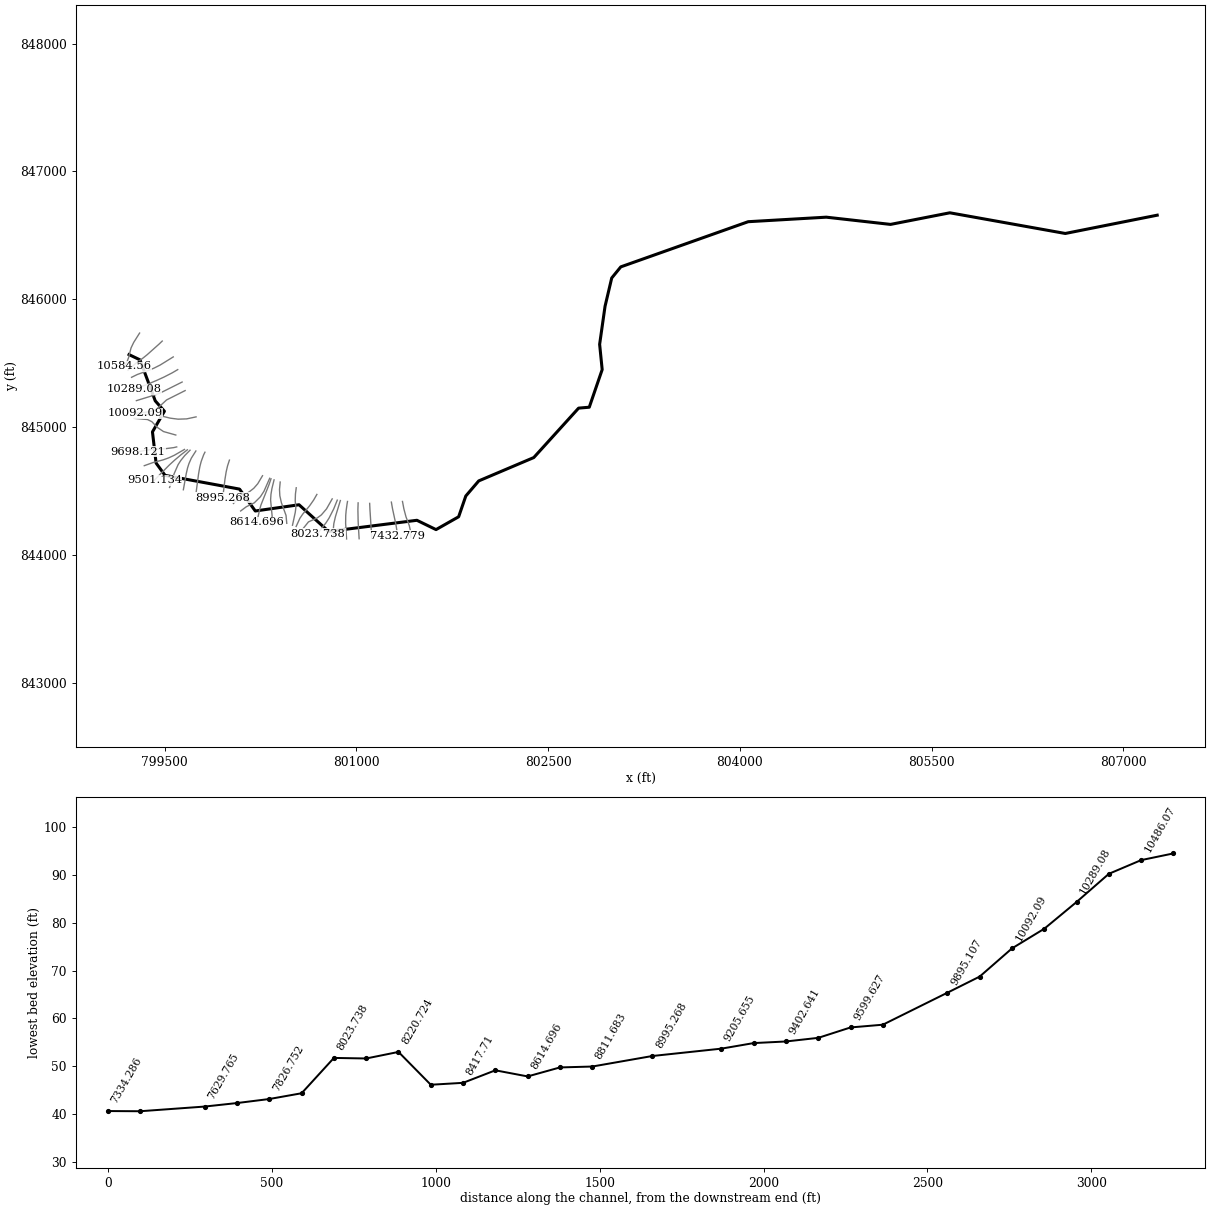
--- 18261_ras.prj (project) ---

Proj Title=18261
Current Plan=p01
Default Exp/Contr=0.3,0.1
English Units
Geom File=g01
Flow File=f01
Plan File=p01
Y Axis Title=Elevation
X Axis Title(PF)=Main Channel Distance
X Axis Title(XS)=Station
BEGIN DESCRIPTION:
RFD model 18261 exported to HEC-RAS
END DESCRIPTION:

--- 18261_ras.p01 (plan) ---

Plan Title=Plan 01
Program Version=4.10
Short Identifier=Plan 01
Geom File=g01
Flow File=f01
Subcritical Flow
Calc Critical at every XS
Secant Critical Depth

--- 18261_ras.f01 (steady flow) ---

Flow Title=Flow 01
Program Version=5.01
Number of Profiles= 6
Profile Names=10yr,25yr,50yr,100yr,100plus,500yr
River Rch & RM=18261,52,10584.56
 1003.97 1644.26 2257.26 2827.22 4127.74 5684.34
River Rch & RM=18261,52,10387.57
 1005.45 1646.73  2260.7 2831.56 4134.08    5692
River Rch & RM=18261,52,10289.08
 1021.75 1673.99 2298.66 2879.66  4204.3 5777.27
River Rch & RM=18261,52,10092.09
 1025.64 1680.49 2307.71 2891.12 4221.04 5797.55
River Rch & RM=18261,52,9895.107
 1027.36 1683.36  2311.7 2896.16  4228.4 5806.42
River Rch & RM=18261,52,9698.121
 1037.28 1699.84 2334.56 2925.02 4270.53 5856.99
River Rch & RM=18261,52,9599.627
 1040.76 1705.62 2342.57 2935.13 4285.29 5874.65
River Rch & RM=18261,52,9402.641
 1042.23 1708.07 2345.97 2939.43 4291.57 5882.21
River Rch & RM=18261,52,9304.148
 1043.68  1710.5 2349.36 2943.72 4297.83 5889.77
River Rch & RM=18261,52,9205.655
 1045.38 1713.34 2353.31 2948.72 4305.13 5898.58
River Rch & RM=18261,52,8995.268
 1046.84 1715.77 2356.69    2953 4311.39 5906.13
River Rch & RM=18261,52,8811.683
  1070.9 1756.04 2412.79 3024.09 4415.17 6031.41
River Rch & RM=18261,52, 8713.19
 1072.84 1759.27 2417.28 3029.77 4423.47 6041.39
River Rch & RM=18261,52,8614.696
 1181.46 1939.24 2666.47 3343.78 4881.92 6581.91
River Rch & RM=18261,52,8516.203
  1182.4 1940.82 2668.67 3346.56 4885.98 6586.73
River Rch & RM=18261,52,8319.217
 1183.58  1942.8 2671.42 3350.04 4891.07 6592.76
River Rch & RM=18261,52,8220.724
 1185.47 1945.96 2675.82 3355.61 4899.19 6602.39
River Rch & RM=18261,52,8122.231
 1186.42 1947.53 2678.01  3358.4 4903.26 6607.21
River Rch & RM=18261,52,8023.738
 1247.77 2050.48  2821.7 3540.76 5169.51 6923.26
River Rch & RM=18261,52,7925.245
 1248.94 2052.43 2824.42  3544.2 5174.54 6929.17
River Rch & RM=18261,52,7728.258
 1251.95 2057.48 2831.46 3553.13 5187.57 6944.52
River Rch & RM=18261,52,7629.765
  1253.1 2059.41 2834.15 3556.54 5192.56 6950.42
River Rch & RM=18261,52,7432.779
 1255.62 2063.64 2840.06 3564.06 5203.52  6963.4
River Rch & RM=18261,52,7334.286
 1264.32 2078.25 2860.48 3589.98 5241.37 7008.15
River Rch & RM=18261,52,7235.793
 1266.61  2082.1 2865.84 3596.79 5251.32 7019.91
River Rch & RM=18261,52,6940.314
 1270.04 2087.86 2873.89 3607.01 5266.23 7037.53
River Rch & RM=18261,52,6743.328
 1272.09 2091.31 2878.71 3613.14 5275.18  7048.1
River Rch & RM=18261,52,6644.834
 1273.01 2092.85 2880.86 3615.86 5279.16 7052.79
River Rch & RM=18261,52,6546.341
 1281.42 2106.99 2900.63 3640.98 5315.84 7096.15
River Rch & RM=18261,52,6349.355
 1286.66  2115.8 2912.93 3656.61 5338.65 7123.05
River Rch & RM=18261,52,6152.369
 1291.43 2123.82 2924.14 3670.85 5359.44 7147.58
River Rch & RM=18261,52,6053.876
 1293.03 2126.49 2927.88  3675.6 5366.37 7155.75
River Rch & RM=18261,52, 5856.89
 1295.51 2130.68 2933.73 3683.04 5377.24 7168.57
River Rch & RM=18261,52,5758.396
 1297.32 2133.72 2937.98 3688.44 5385.13  7177.9
River Rch & RM=18261,52,5659.903
 1311.51 2157.62 2971.42 3730.96 5447.21 7251.16
River Rch & RM=18261,52, 5561.41
 1313.08 2160.26 2975.12 3735.67 5454.08 7259.28
River Rch & RM=18261,52,5294.522
 1314.64  2162.9 2978.81 3740.37 5460.95  7267.4
Boundary for River Rch & Prof#=18261,52,1
Up Type= 0
Dn Type= 2
Boundary for River Rch & Prof#=18261,52,2
Up Type= 0
Dn Type= 2
Boundary for River Rch & Prof#=18261,52,2
Up Type= 0
Dn Type= 2
Boundary for River Rch & Prof#=18261,52,2
Up Type= 0
Dn Type= 2
Boundary for River Rch & Prof#=18261,52,2
Up Type= 0
Dn Type= 2
Boundary for River Rch & Prof#=18261,52,2
Up Type= 0
Dn Type= 2

--- 18261_ras.g01 (geometry) ---

Geom Title=18261
Program Version=4.10

River Reach=18261,52
Reach XY= 30
799222.652373107845567.470152651799308.116333186845526.653860803
  799427.6049833845205.724876905799499.228644194845124.576691199
 799405.84229219844963.155061107799434.112632722  844719.2218575
799504.255536556 844623.04048155800087.012462883 844515.47297987
800210.100669178844344.349153329 800552.28748563844393.032187781
800783.842712403844184.309531769801474.413679362844271.531125544
801623.989149778844198.689533184801800.926919225844299.097512114
801856.829002262844461.500146027801957.998689088844579.611539987
802388.572935792844762.260848329802739.213089974845148.908425254
802822.672393352845156.051200577802923.630475342845450.240024084
802903.725773397845648.042999622802946.023265005845945.369484845
802998.273107648846166.809293947803069.183608293 846253.89236493
804065.662749233846607.200824425804676.484093457846642.619183474
805179.082014055846586.052078616805643.110378088846676.867281219
806546.286228686846515.141577945807265.343586297846658.206623144

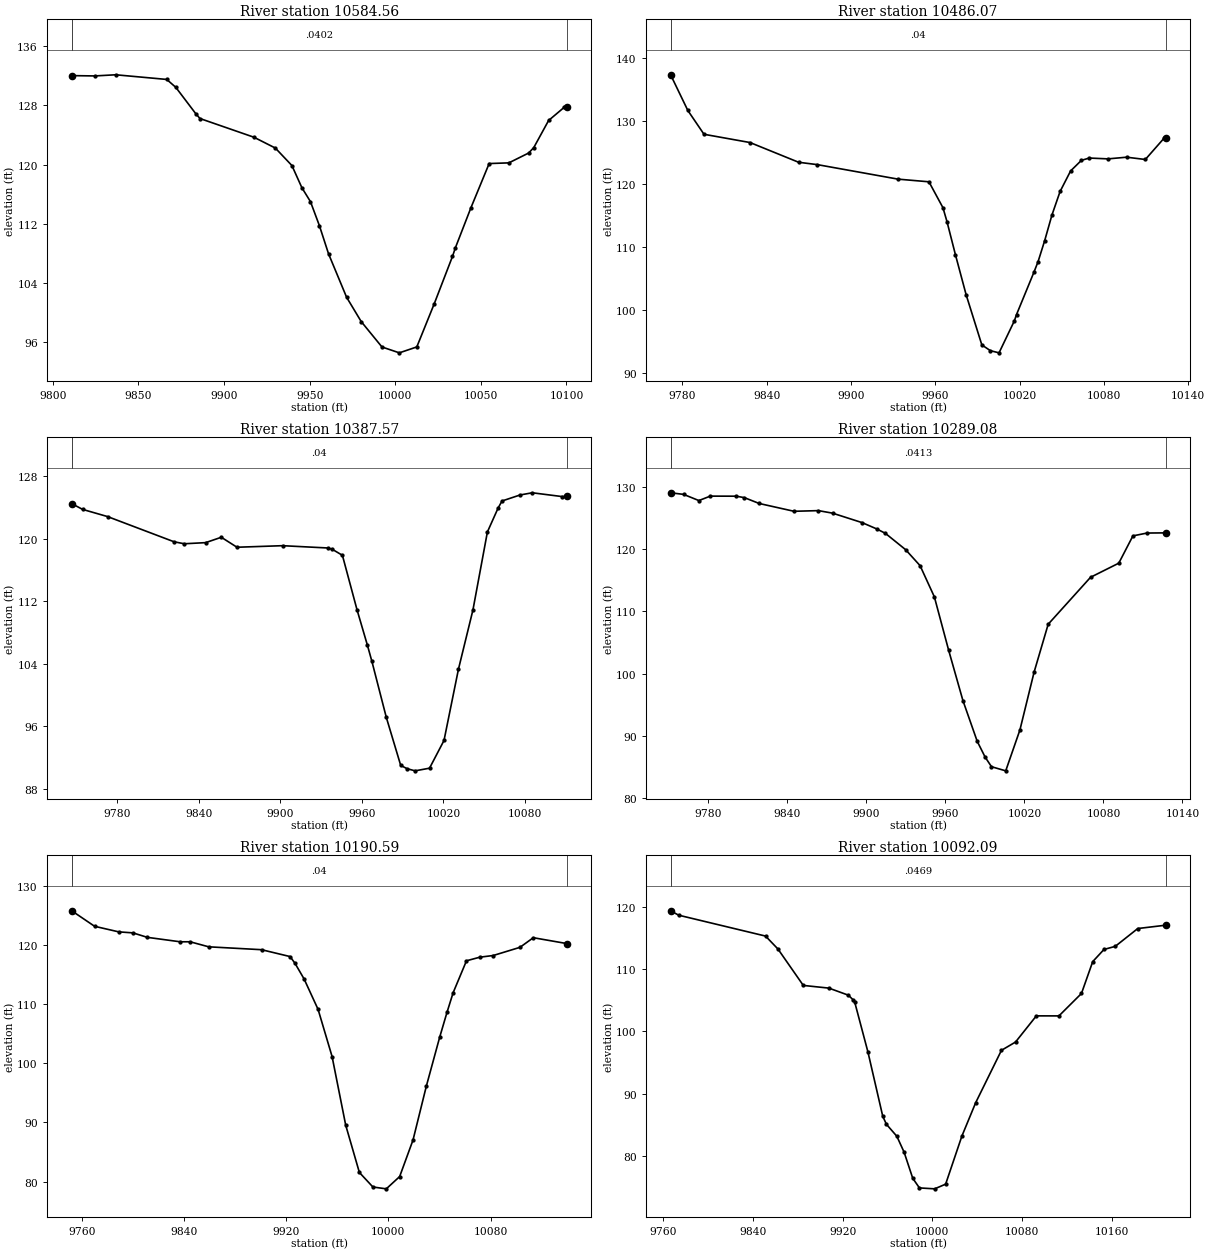
Type RM Length L Ch R = 1 ,10584.56,98.493100,98.493100,98.493100
XS GIS Cut Line= 6
799305.154882385845736.119980314799259.036108711845662.964463771
799238.287245785 845619.74412161799219.034313069845543.983460215
799207.974369439845514.991489081799184.073053142845476.652554076
#Sta/Elev= 30
9811.015132.02359824.543 131.9819836.707132.13719866.528131.50719871.831130.4369
9883.496126.87179885.951126.22279917.463 123.6969929.967122.23259939.648119.8678
9945.478116.86889950.487114.98969955.721 111.7369961.046107.93829971.604102.0619
9980.11398.784089992.25695.34494 10002.494.5535210012.6195.3520110022.81101.1947
10033.46107.590710035.16108.758810044.16 114.12510054.87120.137510066.39 120.231
10077.92121.557610080.94122.295410089.61125.960410098.61127.718510100.13127.7492
#Mann= 3 , 0 , 0
9811.015  0.0402       09811.015  0.0402       010100.13  0.0402       0
#XS Ineff= 2 , 0
       0                               0
Bank Sta=9811.015,10100.13
Exp/Cntr=0.3,0.1

Type RM Length L Ch R = 1 ,10486.07,98.493100,98.493100,98.493100
XS GIS Cut Line= 6
799482.148704576845673.483418524799459.058868618845651.341606537
799364.553854139845566.928164819799330.273925651845539.415912102
 799278.88358068845502.222198188799214.198589227845445.600078411
#Sta/Elev= 30
9771.719137.26329783.975131.59859795.478127.8231 9828.24126.51219862.785123.3839
9876.193123.00519933.505120.70659955.497120.28439965.458116.1764 9968.32113.9815
 9974.38108.68429981.989102.34059993.13494.404569999.24793.4869810005.3793.14832
 10016.398.23808 10017.899.2209910030.22105.953110033.15107.625510037.83110.9437
10042.99115.002210048.79118.747810056.28122.006510063.97 123.68810069.57124.0534
10082.86123.921710096.15124.186410109.44123.823810122.73127.192510123.79127.2422
#Mann= 3 , 0 , 0
9771.719    0.04       09771.719    0.04       010123.79    0.04       0
#XS Ineff= 2 , 0
       0                               0
Bank Sta=9771.719,10123.79
Exp/Cntr=0.3,0.1

Type RM Length L Ch R = 1 ,10387.57,98.493100,98.493100,98.493100
XS GIS Cut Line= 6
799568.424555161845549.478224398799466.154216696845486.071065968
799416.895297723845461.242844789799373.895351818845443.239111233
799287.576755852845412.100802421799242.274480231845389.970762996
#Sta/Elev= 30
9746.404124.46329754.457123.72269772.779122.80749821.784119.57989829.255119.3293
9844.948119.4717 9856.53120.15969868.068118.88379901.663119.08289934.833118.7905
9938.102118.63169945.674117.85269956.515 110.8359963.995106.40269967.357104.3044
9977.98897.122919988.59390.977739993.30190.551349999.19690.2778810009.8290.61742
10020.4794.1628710031.12 103.29110041.77110.857910052.42120.840310060.32123.9073
10063.19124.8023 10076.5 125.57210085.45125.8516 10107.7125.360110110.74125.3901
#Mann= 3 , 0 , 0
9746.404    0.04       09746.404    0.04       010110.74    0.04       0
#XS Ineff= 2 , 0
       0                               0
Bank Sta=9746.404,10110.74
Exp/Cntr=0.3,0.1

Type RM Length L Ch R = 1 ,10289.08,98.493100,98.493100,98.493100
XS GIS Cut Line= 6
799603.510857827845450.220920834799559.369519026845424.391569115
799495.468253404845391.655410743799436.002876364845364.511150078
799361.960880479845333.786154537799261.915665978845295.151245639
#Sta/Elev= 30
9751.431129.06039761.292128.80249772.878127.80999781.569128.52369801.369128.5116
9807.484128.2751 9818.72127.33839845.105126.08619863.663126.19219874.373125.7856
9896.873124.25949907.865123.25589914.482122.5441 9929.85119.91629940.828117.3462
9951.671112.33379962.515103.75929973.35895.666749984.20289.122989990.19786.58806
9995.04685.0391110005.8584.3765710016.6390.9530910027.37100.227610038.09107.9367
10070.25115.480310091.69117.750310102.41122.133910113.13122.590210127.15122.6174
#Mann= 3 , 0 , 0
9751.431  0.0413       09751.431  0.0413       010127.15  0.0413       0
#XS Ineff= 2 , 0
       0                               0
Bank Sta=9751.431,10127.15
Exp/Cntr=0.3,0.1

Type RM Length L Ch R = 1 ,10190.59,98.493000,98.493000,98.493000
XS GIS Cut Line= 6
799637.872627418845353.013283206799487.365300149845277.661304888
799456.435939531845263.660897787799429.349120498 845253.45087625
799414.435274948845248.793826696799280.085837951845207.433174081
#Sta/Elev= 30
9752.162125.76149770.061  123.149788.924122.19889800.108122.02699811.291 121.273
9837.074120.52119844.841 120.5239859.411119.67049900.757119.18519923.075118.0235
9926.932 116.8899934.051114.24359945.028109.08899955.963101.1359 9966.6589.52116
9977.33781.540479987.93279.080979998.408 78.772210008.87 80.846810019.3387.02427
10029.7996.1544410040.26104.443110045.93108.596310050.72111.906610061.18117.3107
10071.65117.920110082.11118.202510103.04119.5837 10113.5121.210110139.57120.2268
#Mann= 3 , 0 , 0
9752.162    0.04       09752.162    0.04       010139.57    0.04       0
#XS Ineff= 2 , 0
       0                               0
Bank Sta=9752.162,10139.57
Exp/Cntr=0.3,0.1

Type RM Length L Ch R = 1 ,10092.09,98.493100,98.493100,98.493100
XS GIS Cut Line= 6
799661.500699538845286.170710781799515.890144317845212.862838354
799443.497352608845145.805271036799421.510222592845131.590990954
799381.581659093845120.345899145799270.369164856 845109.21246359
#Sta/Elev= 30
9766.531119.43259773.731118.72129851.261115.35879862.337113.27279884.948107.4117
9907.793106.9779  9925.2105.83749929.622105.0509 9930.74104.78289942.61996.69819
9955.85886.335319959.14885.045219968.41783.121489974.92380.549099982.609 76.3581
9988.57774.8025310002.1574.6535810011.96 75.407110026.4783.1483210038.7688.51978
10061.7896.9604910074.3598.2952410092.92102.508710113.08102.504110133.18106.1134
10143.23111.244810153.28113.202910163.33113.703310183.43116.573110208.18117.1058
#Mann= 3 , 0 , 0
9766.531  0.0469       09766.531  0.0469       010208.18  0.0469       0
#XS Ineff= 2 , 0
       0                               0
Bank Sta=9766.531,10208.18
Exp/Cntr=0.3,0.1

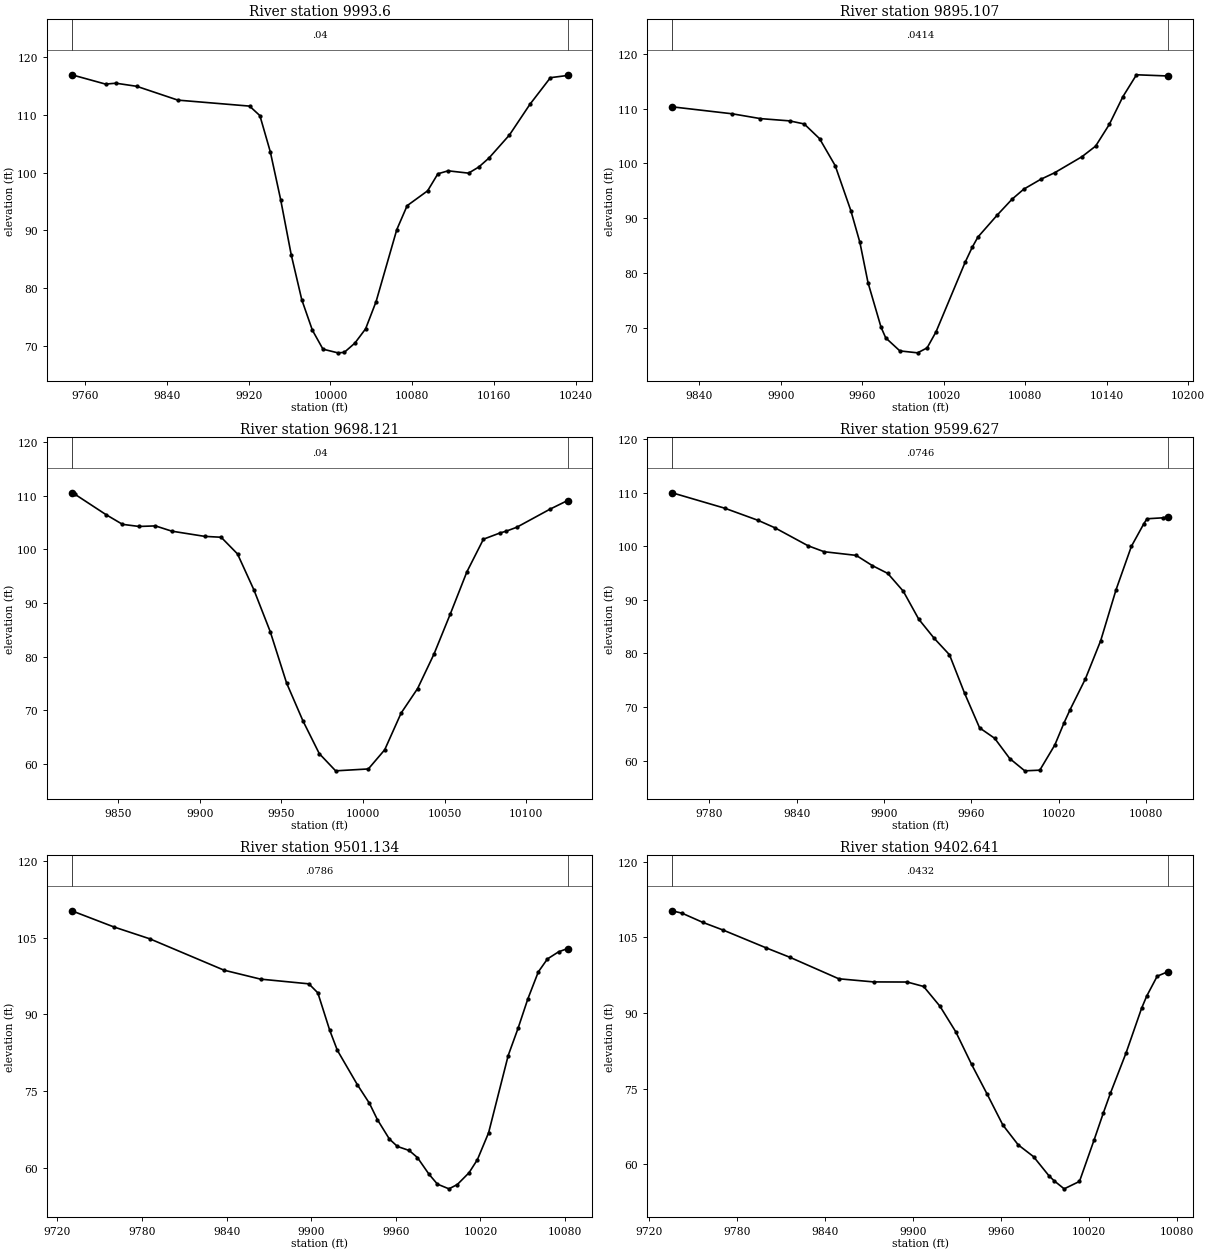
Type RM Length L Ch R = 1 ,  9993.6,98.493100,98.493100,98.493100
XS GIS Cut Line= 6
799746.988979429845080.491058138799673.453113862845064.802768309
799606.508630725845062.510082024799543.859338427845070.591861235
799427.279311909845099.782769881799268.256043074845099.268361102
#Sta/Elev= 30
9746.877116.96089779.903115.34589790.074115.49859810.416114.96349850.702112.5667
9920.842111.52979930.959109.8786 9941.11103.63329951.26195.329599961.59485.77507
 9971.9577.953639982.30672.686029992.66369.3906810007.1868.7511610013.4968.82603
10023.9470.44553 10034.472.9150810044.6477.6265610064.9390.1231810075.04 94.2638
10095.0996.8447110105.1299.7927210115.14100.309810135.1499.9069810145.15100.9696
10155.15102.530610175.16106.525510195.17111.834110215.23116.457210232.03116.8429
#Mann= 3 , 0 , 0
9746.877    0.04       09746.877    0.04       010232.03    0.04       0
#XS Ineff= 2 , 0
       0                               0
Bank Sta=9746.877,10232.03
Exp/Cntr=0.3,0.1

Type RM Length L Ch R = 1 ,9895.107,196.986200,196.986200,196.986200
XS GIS Cut Line= 6
799588.335033301844938.575612055799492.339095036844965.580628469
799444.280135651844997.828213291799400.884801452845042.868453024
799367.031810872845059.706467749799261.854511289845069.143505676
#Sta/Elev= 30
9820.019110.32949864.273109.05649885.006108.17729906.502107.76139917.251107.2008
9928.554104.51439940.05899.581469951.56291.379139958.25485.544989964.22478.20143
9973.81570.055889977.27668.100059987.67565.7244310000.7365.3707310007.7366.27738
10014.3269.2200610035.6981.9025410040.9584.6669210045.1286.5240310059.4990.58794
10070.2493.4418610078.8695.2789110091.2797.0670810101.5898.2779410121.74101.2172
10131.79103.149310141.83107.103110151.87112.187510161.87116.186810185.03115.9665
#Mann= 3 , 0 , 0
9820.019  0.0414       09820.019  0.0414       010185.03  0.0414       0
#XS Ineff= 2 , 0
       0                               0
Bank Sta=9820.019,10185.03
Exp/Cntr=0.3,0.1

Type RM Length L Ch R = 1 ,9698.121,98.493100,98.493100,98.493100
XS GIS Cut Line= 6
799595.405155623844845.451488946 799572.41067215844840.102520613
799514.578765149844832.552762073799401.648558052844825.058187125
799349.276800613844818.655026478799294.493643537844807.403821439
#Sta/Elev= 29
9821.514110.57589823.507110.28659842.464106.50259852.596104.68429862.681104.2891
9872.766104.39169882.851103.40749903.021 102.4359913.045102.27379923.066 99.1609
9933.08892.467589943.10984.665419953.13175.068039963.15268.000719973.17461.87712
9983.19558.6637810003.2459.0178710013.26 62.595510023.3269.44844 10033.474.01491
10043.4780.4698510053.5588.0222510063.6295.8166210073.75101.909610083.96  103.08
10087.55103.388510094.17104.138110114.59107.523810125.31109.1264
#Mann= 3 , 0 , 0
9821.514    0.04       09821.514    0.04       010125.31    0.04       0
#XS Ineff= 2 , 0
       0                               0
Bank Sta=9821.514,10125.31
Exp/Cntr=0.3,0.1

Type RM Length L Ch R = 1 ,9599.627,98.493100,98.493100,98.493100
XS GIS Cut Line= 6
 799656.05245766844825.775607591799577.409053037844780.520981844
799533.179930485844759.967644642799490.140426788844744.409430853
799408.900721594844722.813513866799341.764457208 844698.61313968
#Sta/Elev= 30
9754.386110.00669790.571107.12419813.504104.8561 9824.97103.47469847.797100.1161
9858.82499.001979880.87898.319539891.90596.42325 9902.6194.945589913.24491.63376
9923.87786.40762 9934.5182.829349944.99979.76348 9955.3572.604289965.702 66.1149
9976.05464.167859986.405 60.38979996.75758.0900410007.09 58.216810017.4362.92936
10023.7467.0452510027.8569.48801 10038.475.2512210048.9482.3987210059.4991.90492
10070.04100.012910078.66104.266310080.79105.153910091.64105.332210095.15105.5633
#Mann= 3 , 0 , 0
9754.386  0.0746       09754.386  0.0746       010095.15  0.0746       0
#XS Ineff= 2 , 0
       0                               0
Bank Sta=9754.386,10095.15
Exp/Cntr=0.3,0.1

Type RM Length L Ch R = 1 ,9501.134,98.493100,98.493100,98.493100
XS GIS Cut Line= 6
799678.691860446844822.708333664799628.137700105844783.470628066
799578.635744894844741.456478267799539.488915981844705.678086089
799470.592533328844636.511361286799420.576788503844584.719033057
#Sta/Elev= 30
9730.185110.26669760.175 107.0929785.493104.78859838.17798.652379864.033  96.906
9898.32395.985459904.67594.219029913.09786.916019918.51282.992179932.704 76.2636
9941.28272.621799946.89669.445859955.37465.663259961.08864.200339969.46763.40577
 9975.2862.03053 9983.5658.747519989.47356.832489997.65255.9102810003.5756.75164
10011.87 59.046810017.8261.6095410025.77 66.871610039.6781.9758510046.6187.25513
10053.5793.0157710061.0198.3133110067.48100.8499 10075.4102.242110081.77102.8841
#Mann= 3 , 0 , 0
9730.185  0.0786       09730.185  0.0786       010081.77  0.0786       0
#XS Ineff= 2 , 0
       0                               0
Bank Sta=9730.185,10081.77
Exp/Cntr=0.3,0.1

Type RM Length L Ch R = 1 ,9402.641,98.493100,98.493100,98.493100
XS GIS Cut Line= 6
799699.785994548 844819.85041872799658.813311961844778.464428933
799626.935446868 844738.76024248 799606.33857157 844706.52034221
799576.103475524844637.901598396799539.736057076844528.250146309
#Sta/Elev= 29
9735.994110.29749742.819109.81019756.891107.99849770.962106.44959800.322102.9158
9816.294101.07289849.61196.812189873.344 96.18929896.294 96.1658 9907.4895.28448
9918.66791.347239929.44186.272479940.15779.846479950.87373.885839961.513 67.8049
 9971.9763.874199982.42761.532599992.88357.760849996.46956.7474610003.3255.15033
10013.7656.6253110023.8164.9211610030.1270.2829610034.8574.1171110045.48 82.0776
10056.1190.9654410059.5893.3686710066.7497.3230410074.0798.21355
#Mann= 3 , 0 , 0
9735.994  0.0432       09735.994  0.0432       010074.07  0.0432       0
#XS Ineff= 2 , 0
       0                               0
Bank Sta=9735.994,10074.07
Exp/Cntr=0.3,0.1

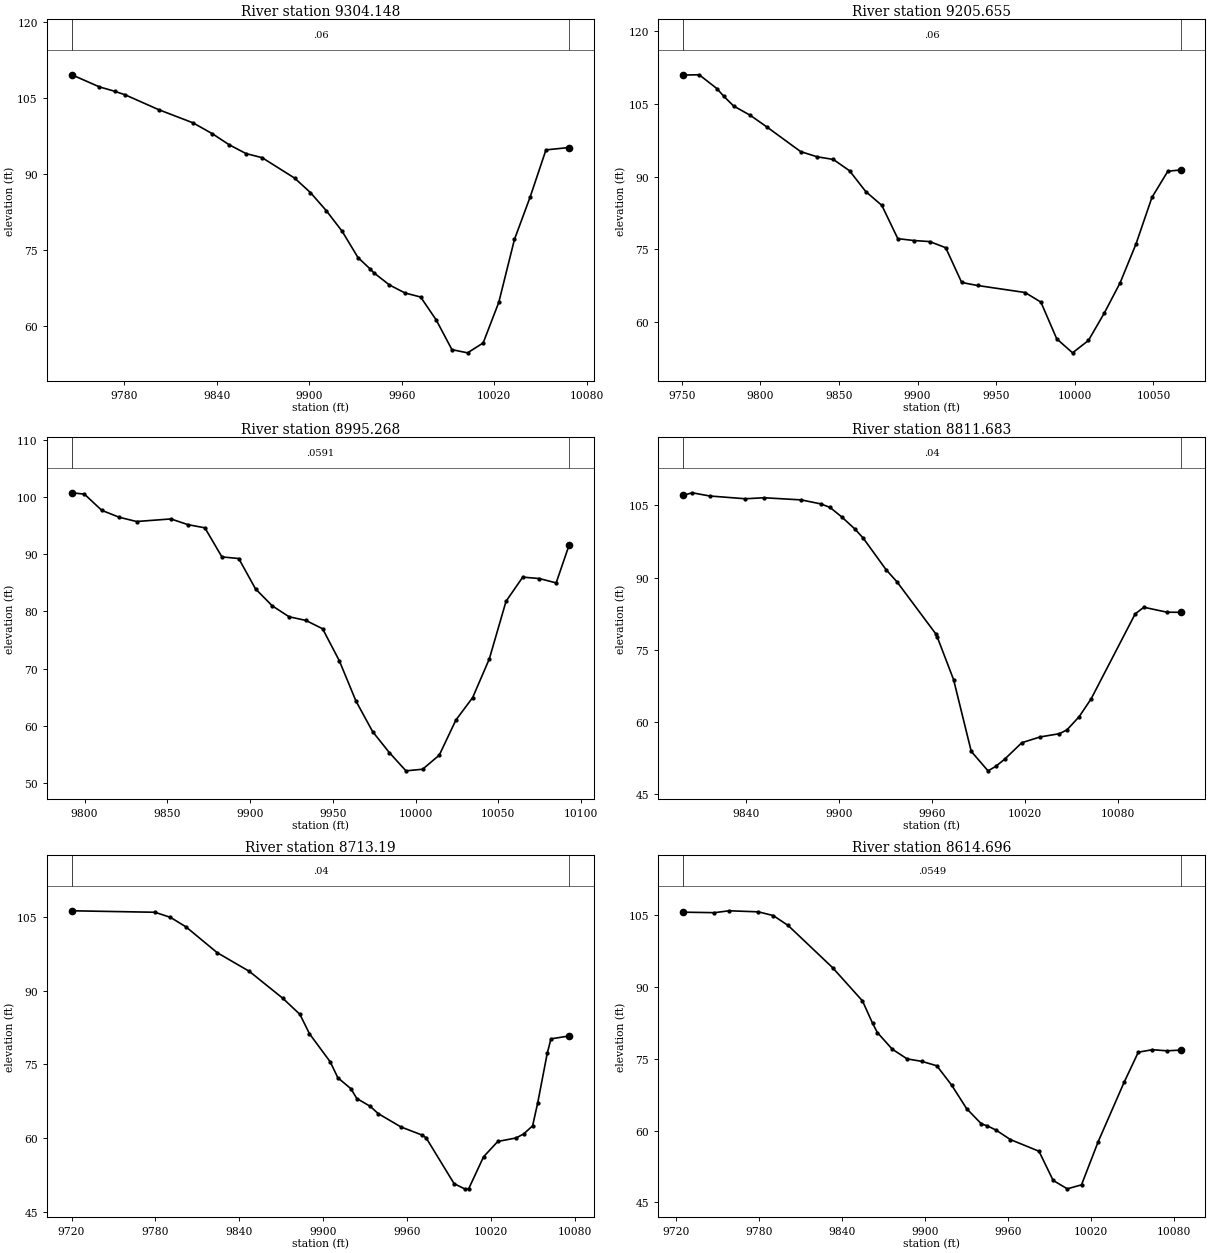
Type RM Length L Ch R = 1 ,9304.148,98.493100,98.493100,98.493100
XS GIS Cut Line= 6
799745.378238231844813.673405058 799709.74101302844757.282870307
799691.162914761844714.891975623799680.577162651844681.757333613
 799670.24070595 844637.17031113 799647.44849559844510.298073223
#Sta/Elev= 29
 9746.05109.53439763.842107.16149773.739106.29739780.768105.57629802.372102.6681
9824.644100.07669837.16197.93794 9848.0895.766279858.99894.03337  9869.593.21627
9890.49689.208999900.83786.346089911.10282.791269921.36778.736849931.63273.57576
 9939.6771.28512 9941.8770.588549952.01168.178199962.15166.593729972.291 65.7976
9982.43161.263679992.57255.4443610002.7154.8137710012.8456.7570410022.9864.76005
10033.1377.1301210043.3585.5127510053.5794.75313 10068.6 95.2183
#Mann= 3 , 0 , 0
 9746.05    0.06       0 9746.05    0.06       0 10068.6    0.06       0
#XS Ineff= 2 , 0
       0                               0
Bank Sta=9746.05,10068.6
Exp/Cntr=0.3,0.1

Type RM Length L Ch R = 1 ,9205.655,210.387200,210.387200,210.387200
XS GIS Cut Line= 6
799816.292032154844804.065729749799806.070098596844783.705717939
799786.816703709844731.115915414799776.380883152844690.339670899
799766.681247293844635.811768812799748.283850156844497.019108699
#Sta/Elev= 30
9750.949111.00389761.093111.05839772.283108.22279776.843106.58429783.002104.6068
9793.651102.6737  9804.3100.24749825.59895.198269836.04794.12907 9846.3793.57958
9856.69291.246839867.01486.947719877.24884.091689887.40577.224929897.56276.84047
9907.71976.618369917.87675.353319928.02768.176789938.10367.553419968.33466.10561
9978.41164.119969988.48856.534799998.56553.6489510008.6456.2057510018.7161.84896
10028.7968.1045710038.8976.1184110049.0285.7293710059.1591.1469410067.2391.40758
#Mann= 3 , 0 , 0
9750.949    0.06       09750.949    0.06       010067.23    0.06       0
#XS Ineff= 2 , 0
       0                               0
Bank Sta=9750.949,10067.23
Exp/Cntr=0.3,0.1

Type RM Length L Ch R = 1 ,8995.268,183.585200,183.585200,183.585200
XS GIS Cut Line= 6
800007.814149429 844742.20196706799993.143519401844697.134216264
799982.656546117844652.035460767799972.824804234844591.909864009
799963.465121077844511.480021269799954.728957626844447.230786578
#Sta/Elev= 30
9792.348100.76899799.922100.53299810.43897.693349820.95596.486719831.47195.74067
9852.20196.192279862.46895.194099872.73594.634119883.00289.549949893.174 89.2634
9903.30783.95577 9913.4480.978119923.57379.074219933.70578.433429943.83876.97205
9953.92671.382389963.99464.325229974.06158.972259984.12955.311529994.19652.10863
10004.2652.3880110014.3354.85798 10024.461.0165810034.4864.9189810044.5771.70431
10054.6781.7838210064.7686.0094810074.8585.7575310084.9484.9953710092.7891.62469
#Mann= 3 , 0 , 0
9792.348  0.0591       09792.348  0.0591       010092.78  0.0591       0
#XS Ineff= 2 , 0
       0                               0
Bank Sta=9792.348,10092.78
Exp/Cntr=0.3,0.1

Type RM Length L Ch R = 1 ,8811.683,98.493100,98.493100,98.493100
XS GIS Cut Line= 6
800266.673941977844620.132637989800229.611852185844557.690872151
800197.962817402844521.537881174800162.226222906844493.693059377
800084.599114408 844450.43371941800039.451583879844403.215039536
#Sta/Elev= 30
9799.439107.0926 9805.22107.61859816.482106.95229839.538106.37669851.476106.5874
9875.578106.14019888.355105.29639894.162104.5683 9901.68102.60579910.008100.1418
9915.46398.233519930.29291.652949937.29389.146559962.22278.391649963.30177.68002
 9973.8468.823479985.22553.937549996.05649.89912   1000150.8171210006.9152.35334
10017.8555.7355610029.6856.9383510042.1157.6062210046.9758.4031510054.8661.14576
10062.5864.8499710090.96 82.463710096.5783.8550910111.4982.8301610120.2682.80619
#Mann= 3 , 0 , 0
9799.439    0.04       09799.439    0.04       010120.26    0.04       0
#XS Ineff= 2 , 0
       0                               0
Bank Sta=9799.439,10120.26
Exp/Cntr=0.3,0.1

Type RM Length L Ch R = 1 , 8713.19,98.493100,98.493100,98.493100
XS GIS Cut Line= 6
800322.731496271844600.093964733800277.924632816844498.562656959
800249.472001115844454.835473106800202.358417117844408.060072885
800140.352199263844377.826721116800095.515865246844344.290335646
#Sta/Elev= 30
9720.211106.19599779.606105.89469790.693104.85779801.827102.92449824.094 97.6889
9847.08393.893449870.99388.425789883.26885.150059890.08581.220059904.87975.53297
9910.38772.276969919.67270.061699923.95768.055449933.58466.466539939.121 65.0153
9955.49962.282159970.89160.603579973.47160.078019993.50350.76391   1000149.71242
10003.9449.7420310014.5756.2356310024.7559.3401710037.74 60.044210043.2960.87123
10049.6162.51627 10053.367.2233610060.04 77.211510062.7480.1758410075.7280.77197
#Mann= 3 , 0 , 0
9720.211    0.04       09720.211    0.04       010075.72    0.04       0
#XS Ineff= 2 , 0
       0                               0
Bank Sta=9720.211,10075.72
Exp/Cntr=0.3,0.1

Type RM Length L Ch R = 1 ,8614.696,98.493100,98.493100,98.493100
XS GIS Cut Line= 6
800333.206884359844596.349368991800316.404845832844547.498794149
800254.431962018844391.072279953800245.924096333844361.204475726
800225.749555381844273.640554379800220.569517005844255.456162348
#Sta/Elev= 30
9725.154105.61629747.731105.51179758.306105.90819779.501105.68669790.257104.9084
9801.014102.83759833.282 93.99999854.79587.079339862.07782.422589865.55180.47747
9876.30777.006639887.06374.975949897.81974.444759908.57673.531819919.33269.47909
9930.08864.597329940.84461.388599945.06960.987729951.38360.10479 9961.7858.11934
9982.48155.682959992.72549.5846210002.9747.8270910013.2448.6624710025.3657.71417
10044.0570.0769910054.3276.3669410064.5976.8955310074.9776.6555310084.8976.80882
#Mann= 3 , 0 , 0
9725.154  0.0549       09725.154  0.0549       010084.89  0.0549       0
#XS Ineff= 2 , 0
       0                               0
Bank Sta=9725.154,10084.89
Exp/Cntr=0.3,0.1

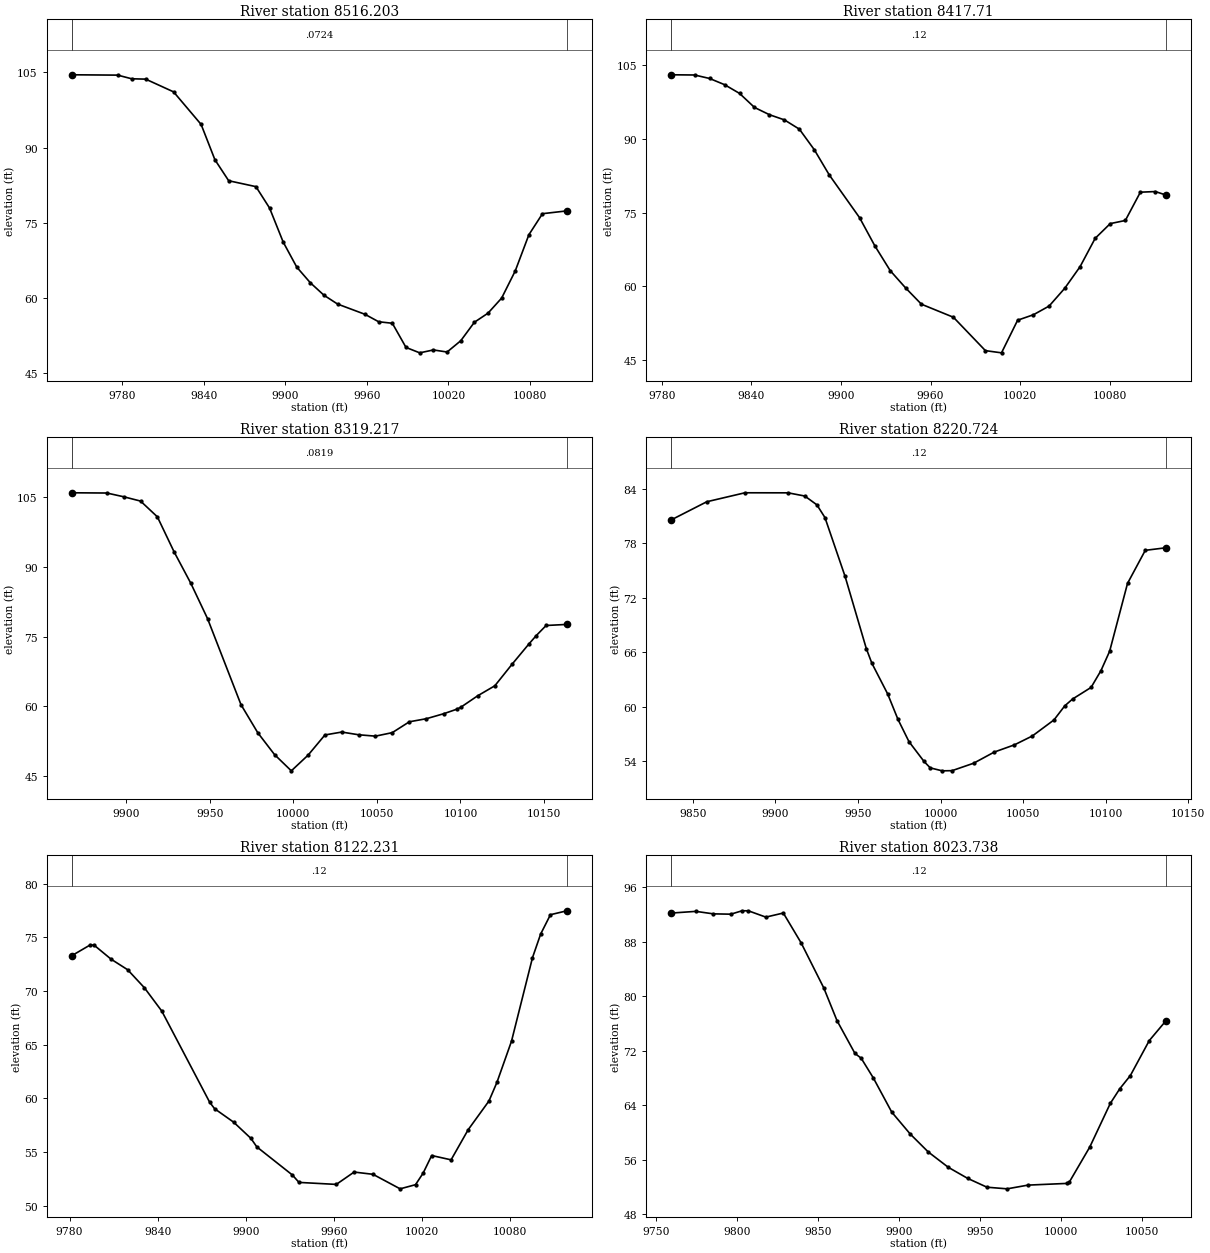
Type RM Length L Ch R = 1 ,8516.203,98.493100,98.493100,98.493100
XS GIS Cut Line= 6
800357.135805664844587.795591691800340.325210336844519.855143148
800332.721622922844474.185927654800329.918354474844429.949418434
800341.640644554844307.937538836800344.605023346844227.031982139
#Sta/Elev= 30
9742.846104.52019776.631104.45079786.932103.72369797.234103.65369817.757101.1159
9838.03394.62434 9848.1787.593029858.30883.405779878.35882.227899888.37877.97035
9898.39871.190999908.41266.184689918.422 63.05959928.43160.583819938.44158.82706
9958.56956.788629968.63655.303999978.70455.003649988.77150.183129998.83949.10894
10008.9249.6848510018.9949.2727610029.0551.5203610039.07 55.2047 10049.157.01854
10059.1260.0186210069.1465.4390810079.1672.6439610089.1676.8379510107.1477.39785
#Mann= 3 , 0 , 0
9742.846  0.0724       09742.846  0.0724       010107.14  0.0724       0
#XS Ineff= 2 , 0
       0                               0
Bank Sta=9742.846,10107.14
Exp/Cntr=0.3,0.1

Type RM Length L Ch R = 1 , 8417.71,98.493100,98.493100,98.493100
XS GIS Cut Line= 6
800405.043406528844570.670250205 800399.58038227844511.915502023
800402.204071947844463.244363783800414.512653079844408.609837603
800450.522765111844310.120379623800456.369149417844247.767462227
#Sta/Elev= 30
9786.132103.03579801.944102.99139812.034102.28339822.058101.02239832.07599.24852
9842.09296.391879852.10794.914499862.12293.861299872.13691.976999882.15187.78676
9892.16682.660399912.44673.976769922.64968.257919933.00763.188839943.36659.65721
9953.853 56.37759975.28453.722669996.71546.93287 10007.546.4854410018.2953.12147
10028.9154.2383310039.3655.9966610049.8259.6092110060.0964.00166 10070.269.76868
10080.31 72.767210090.4173.4037810100.4879.1578910110.4879.2864610117.7178.56928
#Mann= 3 , 0 , 0
9786.132    0.12       09786.132    0.12       010117.71    0.12       0
#XS Ineff= 2 , 0
       0                               0
Bank Sta=9786.132,10117.71
Exp/Cntr=0.3,0.1

Type RM Length L Ch R = 1 ,8319.217,98.493100,98.493100,98.493100
XS GIS Cut Line= 6
800530.496556156844525.825006669800524.234164913844477.290282364
800522.451821406844424.226865193800527.402920812 844370.12715832
800522.878022158844333.997255576800501.147570922844232.841321722
#Sta/Elev= 30
9867.476105.97689888.474 105.9249898.557 105.118 9908.64  104.199918.705100.7961
9928.71193.253419938.71686.482589948.72278.875319968.73360.33951 9978.7754.29286
 9988.8149.58097 9998.8546.0844510008.9149.4784810018.9553.8139110029.0154.43796
10039.09 53.854410049.1753.5555710059.2454.3128510069.4656.6506410079.6857.31558
10089.9158.3772110097.7659.3496510100.1459.7597210110.3762.25661 10120.664.40468
10130.83 69.012810141.0573.4397210145.3875.2178210151.2877.3922110163.7277.62156
#Mann= 3 , 0 , 0
9867.476  0.0819       09867.476  0.0819       010163.72  0.0819       0
#XS Ineff= 2 , 0
       0                               0
Bank Sta=9867.476,10163.72
Exp/Cntr=0.3,0.1

Type RM Length L Ch R = 1 ,8220.724,98.493100,98.493100,98.493100
XS GIS Cut Line= 6
800691.970357041844473.805493512800666.414134002844429.595584883
800634.764992186844384.364702571800581.976607349844320.660246193
 800559.66792773844288.290905876800529.831557596 844223.27999283
#Sta/Elev= 30
 9836.6680.555419858.38282.569449881.48383.556319907.63483.550159917.74483.19871
9925.07782.227399929.94980.830519942.15474.35143 9955.0266.404159958.36764.80245
9967.93261.426419974.175 58.62639980.84356.173379989.98453.989449993.754 53.2827
   1000152.9595110006.94 52.978610020.0153.7969210032.5555.02813 10044.755.81715
10055.5956.7969910068.6958.5624710075.2260.1120310079.93 60.858310091.1662.13977
10097.1363.98134 10102.466.1195110113.23 73.584610123.9977.22406 10136.677.50729
#Mann= 3 , 0 , 0
 9836.66    0.12       0 9836.66    0.12       0 10136.6    0.12       0
#XS Ineff= 2 , 0
       0                               0
Bank Sta=9836.66,10136.6
Exp/Cntr=0.3,0.1

Type RM Length L Ch R = 1 ,8122.231,98.493100,98.493100,98.493100
XS GIS Cut Line= 6
 800811.76767748844438.999515266800767.204116276844360.471048288
800726.917687173844313.582062861800694.747452246844289.840028338
800626.249137536844259.127577431800583.154862363844205.505557904
#Sta/Elev= 30
9781.47973.291589794.25674.309389796.94374.248729808.26772.969839819.592 71.9829
9830.96870.309419842.81968.13624 9875.4859.642369878.81859.045719891.77657.79404
9903.50956.290759907.56855.493619931.82752.872739936.29452.186929961.70852.00042
9973.85853.149899986.71552.94043 10005.251.5878410015.6751.9737410020.8453.04451
 10026.754.6894310039.9154.2877810051.5557.09206 10065.759.7632510071.1361.49372
10081.0765.3309610095.3773.1098410100.9375.3063310107.5977.1075910118.8277.47397
#Mann= 3 , 0 , 0
9781.479    0.12       09781.479    0.12       010118.82    0.12       0
#XS Ineff= 2 , 0
       0                               0
Bank Sta=9781.479,10118.82
Exp/Cntr=0.3,0.1

Type RM Length L Ch R = 1 ,8023.738,98.493100,98.493100,98.493100
XS GIS Cut Line= 6
800851.432327004844429.266388747800823.758502398844360.753019531
800787.206347678844288.791497004800762.517328713844250.705526517
 800713.18364212844188.068997584800700.052190511844166.078292841
#Sta/Elev= 30
9759.28292.174219774.66992.427139785.45492.060889796.23992.014569803.15892.51354
9807.02392.510599817.80891.583679828.59392.183069839.545 87.8193 9853.5681.18421
9861.693 76.39729872.767 71.57699876.59770.879819884.09867.981599895.47562.96017
9906.85159.751189917.97157.11766 9930.3554.860949942.26853.241139954.185 51.9429
9966.62451.703819979.45652.2500710003.5552.50055 10004.952.6654710017.58 57.8356
10030.2664.2498210036.0966.3925210042.6268.3329210054.2773.4598510064.6676.40044
#Mann= 3 , 0 , 0
9759.282    0.12       09759.282    0.12       010064.66    0.12       0
#XS Ineff= 2 , 0
       0                               0
Bank Sta=9759.282,10064.66
Exp/Cntr=0.3,0.1

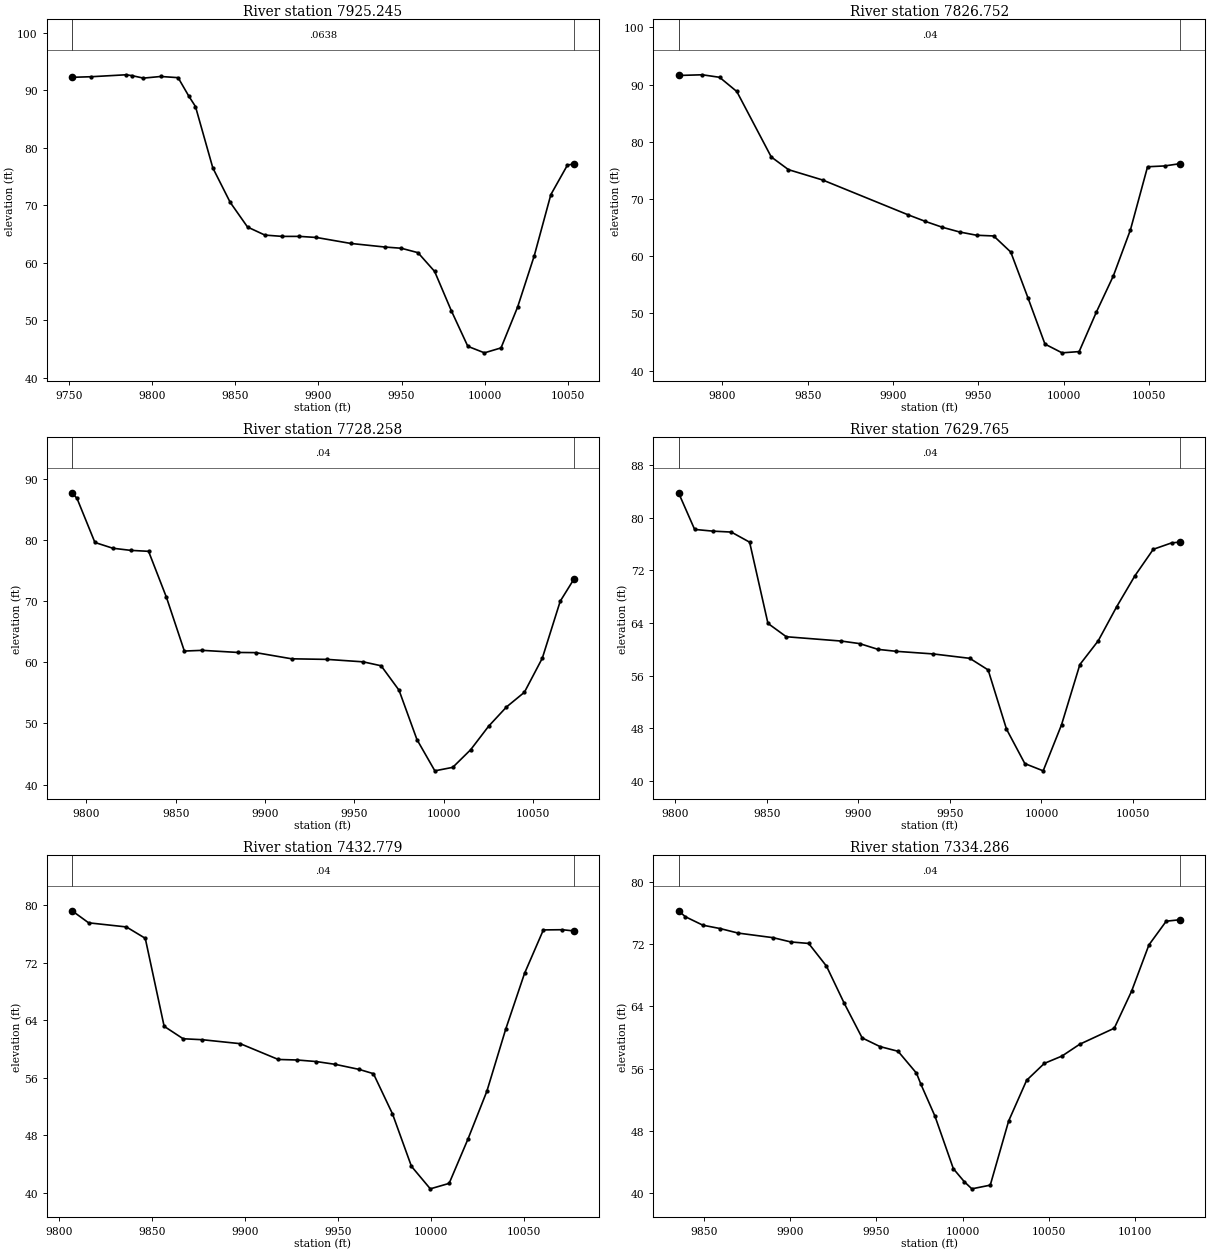
Type RM Length L Ch R = 1 ,7925.245,98.493100,98.493100,98.493100
XS GIS Cut Line= 6
800875.555740444844426.087334262800837.032388939844299.979961905
800824.520515795844245.129213558 800821.70395624844216.396425217
800822.285335274844136.992362364800821.922903644844131.142879793
#Sta/Elev= 30
9751.56692.264489763.15992.367539784.07192.705459787.69792.555219794.52892.12406
9804.98492.40908 9815.4492.203249821.92588.968659825.89687.181859836.35276.49197
9846.80970.503119857.26566.201419867.721 64.80069878.17764.573749888.53464.57326
9898.79164.383239919.305 63.35089939.81662.725989949.86462.508939959.912   61.74
9969.95358.475269979.95351.671749989.95345.436379999.95344.3032310009.9545.16188
10019.9552.2818210029.9561.1854410039.9671.8461510049.9676.9894910053.8277.17798
#Mann= 3 , 0 , 0
9751.566  0.0638       09751.566  0.0638       010053.82  0.0638       0
#XS Ineff= 2 , 0
       0                               0
Bank Sta=9751.566,10053.82
Exp/Cntr=0.3,0.1

Type RM Length L Ch R = 1 ,7826.752,98.493100,98.493100,98.493100
XS GIS Cut Line= 6
800931.481978611844418.717209851800928.089291516844399.104914257
800921.091447213844348.650678802800917.662831835  844310.5358194
800916.778406593844248.879779524800924.176837906 844125.83696231
#Sta/Elev= 24
 9774.2991.596389788.21191.717769798.33891.277319808.433 88.79419828.62577.34666
9838.72175.126089858.83773.307979908.93867.216469918.93966.07843 9928.9465.04854
9938.941 64.23229948.948 63.65799958.96363.534579968.97960.712689978.99552.75656
 9989.0144.626659999.02643.0965210009.0543.3151510019.0750.1807310029.09 56.5558
10039.1164.6181210049.1375.6360710059.1575.7771510068.3376.18427
#Mann= 3 , 0 , 0
 9774.29    0.04       0 9774.29    0.04       010068.33    0.04       0
#XS Ineff= 2 , 0
       0                               0
Bank Sta=9774.29,10068.33
Exp/Cntr=0.3,0.1

Type RM Length L Ch R = 1 ,7728.258,98.493100,98.493100,98.493100
XS GIS Cut Line= 6
801014.560987141844407.768813376 801012.82350599 844354.75171119
801014.619830999844266.148069114 801018.10408264844200.973581287
801018.224857848844198.977231281801022.419335804844127.384088269
#Sta/Elev= 26
9792.06587.685089794.83586.761829804.84179.566749814.84678.623839824.85178.27527
9834.85778.119139844.86270.592129854.86461.822889864.86661.93918 9884.8761.59411
9894.87361.564669914.87760.557319934.88260.458889954.91160.059469964.925 59.4155
9974.93955.423859984.95447.363549994.96842.2504110004.9842.82156   10015  45.701
10025.0249.5320610035.0452.6874710045.05  55.08610055.0760.6550610065.0969.96448
10072.7273.55966
#Mann= 3 , 0 , 0
9792.065    0.04       09792.065    0.04       010072.72    0.04       0
#XS Ineff= 2 , 0
       0                               0
Bank Sta=9792.065,10072.72
Exp/Cntr=0.3,0.1

Type RM Length L Ch R = 1 ,7629.765,196.986200,196.986200,196.986200
XS GIS Cut Line= 5
801104.797965527844403.773552058801106.782100163844360.518466111
801116.417432219844206.921343586801116.538207428844204.924993579
801121.021167611844130.248889472
#Sta/Elev= 25
  9801.883.789289810.58378.219819820.594 77.95619830.60477.816869840.61576.28041
 9850.6363.93182 9860.6561.902739890.70961.245269900.729  60.8589910.74859.98114
9920.76859.684019940.80759.290949960.84658.619729970.86656.855699980.886 47.8603
9990.90542.6167610000.9241.5158510010.9448.5172310020.9657.6800410030.98 61.2857
   1004166.4402110051.01   71.1710061.0375.1950310071.0576.1710210075.8176.29645
#Mann= 3 , 0 , 0
  9801.8    0.04       0  9801.8    0.04       010075.81    0.04       0
#XS Ineff= 2 , 0
       0                               0
Bank Sta=9801.8,10075.81
Exp/Cntr=0.3,0.1

Type RM Length L Ch R = 1 ,7432.779,98.493100,98.493100,98.493100
XS GIS Cut Line= 6
801274.566455371844413.759933808801283.466868608 844362.63986967
 801309.89822103844239.752863681801312.314558482844225.755940399
801312.633265466844223.781497222801324.713336949844148.821093776
#Sta/Elev= 25
 9807.2179.201449816.10177.527829836.40276.954369846.553  75.3739856.70363.13583
9866.91361.405729877.14261.273099897.59960.721799918.05758.525069928.28558.45046
9938.51458.233879948.74357.843959961.50257.14461  9969.256.548169979.42950.96942
9989.61943.671049999.76640.5345510009.8941.2933810020.0247.4626410030.1554.09167
10040.2862.7221410050.41 70.490810060.5476.5400810070.6776.5677610076.9376.39884
#Mann= 3 , 0 , 0
 9807.21    0.04       0 9807.21    0.04       010076.93    0.04       0
#XS Ineff= 2 , 0
       0                               0
Bank Sta=9807.21,10076.93
Exp/Cntr=0.3,0.1

Type RM Length L Ch R = 1 ,7334.286,98.493100,98.493100,98.493100
XS GIS Cut Line= 6
801361.530209728844418.875448767801372.466160823844361.092766098
801388.906741737844298.757132492801414.574469106844230.552329673
801422.256519333844196.618595632801427.284506485844136.830692502
#Sta/Elev= 30
9835.27476.253699839.21975.492499849.39674.403149859.57473.964439869.75173.39452
9890.10672.801659900.38472.254429910.726 72.06349921.06869.14877 9931.4164.35884
9941.752 59.93939952.09458.827559962.56658.224539973.25555.415569975.80153.99745
9983.94449.908379994.63343.15752   1000141.4828910005.3640.5734210016.0341.04808
10026.6949.2815210037.1254.5023310047.3856.6702410057.6357.6138110067.8559.12111
10087.94 61.184910097.9965.9410410108.0371.8728410118.0674.9158910126.2475.10779
#Mann= 3 , 0 , 0
9835.274    0.04       09835.274    0.04       010126.24    0.04       0
#XS Ineff= 2 , 0
       0                               0
Bank Sta=9835.274,10126.24
Exp/Cntr=0.3,0.1