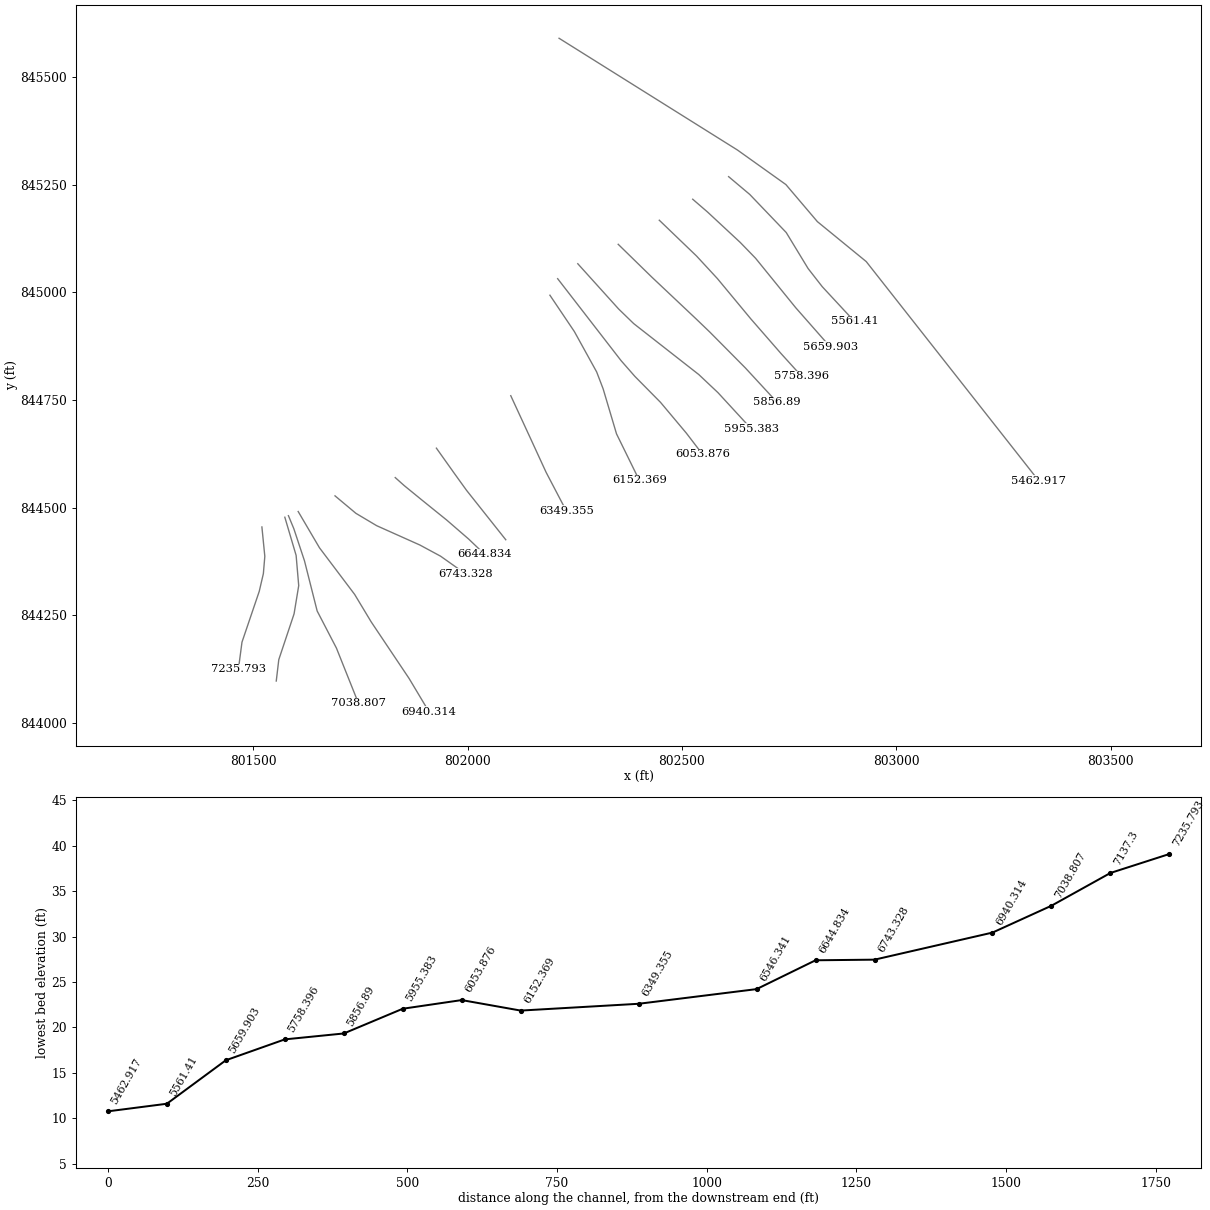
HEC-RAS study 18261_ras.prj: 18261

--- 18261_ras.g01 (geometry) --- (continued)

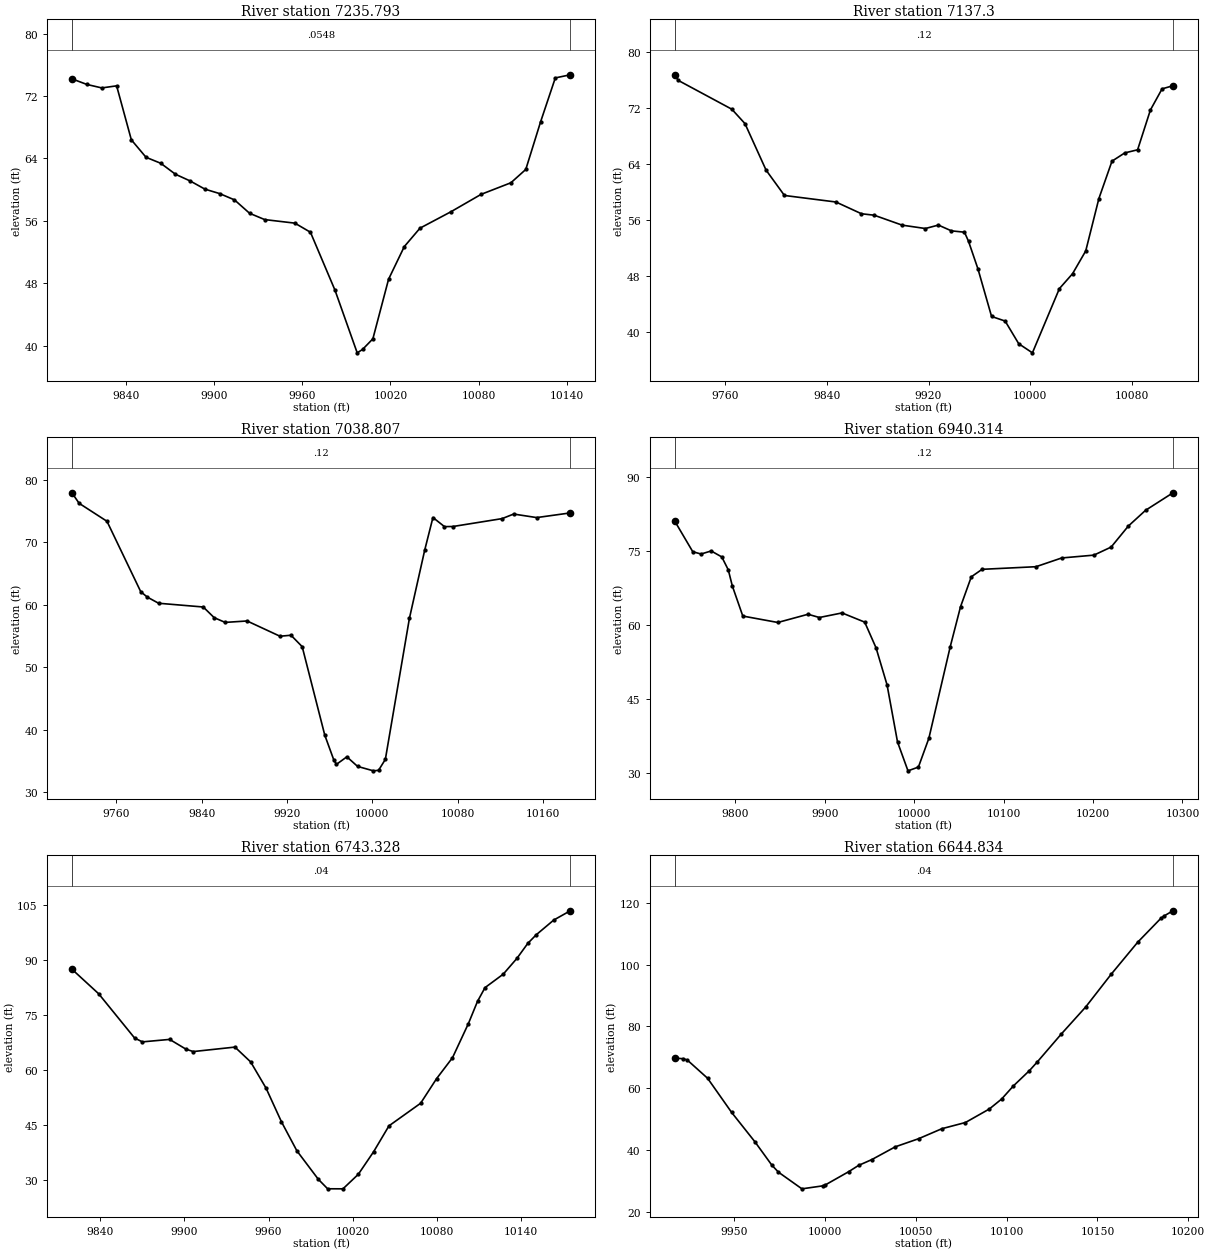
Type RM Length L Ch R = 1 ,7235.793,98.493100,98.493100,98.493100
XS GIS Cut Line= 6
 801520.51986368844455.037110589801527.313080653844386.766469197
801523.923214355844346.623636463 801514.28433257 844305.48070304
801474.065252426844187.620889938801465.739666938844124.852855641
#Sta/Elev= 30
 9803.1574.201419813.34373.481279823.499 73.03619833.60173.302729843.61466.38486
9853.62764.14447 9863.6463.379639873.65761.972719883.69261.110499893.72860.06391
9903.76459.493269913.83758.688459924.10856.972469934.37956.164249954.93755.70826
9965.54454.541469982.26647.108279997.36639.08874   1000139.5214110008.0440.88632
10018.7348.5247610029.4352.7045210040.1355.0671610061.0357.1523810081.7159.39731
   1010260.8823610112.1362.5901110122.18 68.672810132.2374.3187710142.4274.72027
#Mann= 3 , 0 , 0
 9803.15  0.0548       0 9803.15  0.0548       010142.42  0.0548       0
#XS Ineff= 2 , 0
       0                               0
Bank Sta=9803.15,10142.42
Exp/Cntr=0.3,0.1

Type RM Length L Ch R = 1 ,  7137.3,98.493100,98.493100,98.493100
XS GIS Cut Line= 6
 801573.96344601 844477.68269633801600.301641593844388.998111209
801606.356553949844318.808013357801595.510242456 844253.31780482
801559.890534406844147.022927588801553.988126746844097.365630457
#Sta/Elev= 30
9720.29676.755579723.14875.953219765.29171.832359775.63869.771939792.22863.12279
9806.67759.499379847.15358.565149867.24756.885189877.24856.676459899.23555.25656
9917.48654.775049927.74155.266089937.99654.439329948.252 54.24829951.42452.95295
9958.86648.990719969.55242.204589980.23941.541089990.92538.2996710001.6836.99899
 10022.946.1835110033.25 48.313710043.6151.5690310053.9659.0648510064.2664.40463
10074.3365.58636 10084.466.0292310094.4771.7209710103.6574.7434110112.2375.18979
#Mann= 3 , 0 , 0
9720.296    0.12       09720.296    0.12       010112.23    0.12       0
#XS Ineff= 2 , 0
       0                               0
Bank Sta=9720.296,10112.23
Exp/Cntr=0.3,0.1

Type RM Length L Ch R = 1 ,7038.807,98.493100,98.493100,98.493100
XS GIS Cut Line= 6
801582.367947743844481.243925879801594.975493642844450.969768717
801619.788473182844376.457070943801649.356009891844259.977791169
801694.275634148 844173.85126172801745.758007299844045.528335577
#Sta/Elev= 30
9718.42977.900219725.19376.215039751.30173.336679782.95262.065689789.13561.19787
9799.67560.217699841.52959.617049851.80257.906299862.07557.152389882.62257.38029
9913.44154.938269923.78555.096769934.25753.268849955.43539.101579963.88435.13496
9966.37834.429839976.13335.638189986.17134.10192   1000133.3922610005.8333.47743
 10012.235.2275910034.7557.7993610049.1568.76974 10056.873.94285 10067.672.48171
10075.5572.5018510121.6373.7643710132.43 74.495310154.0473.9302410185.5174.67719
#Mann= 3 , 0 , 0
9718.429    0.12       09718.429    0.12       010185.51    0.12       0
#XS Ineff= 2 , 0
       0                               0
Bank Sta=9718.429,10185.51
Exp/Cntr=0.3,0.1

Type RM Length L Ch R = 1 ,6940.314,196.986200,196.986200,196.986200
XS GIS Cut Line= 6
801605.112720823844490.881541594801654.772516929844406.675707739
801736.736514193844298.483027233 801775.38854454844234.599543837
801863.745991654844103.262490215801910.564648154844025.347930576
#Sta/Elev= 30
9731.97481.157749752.304 74.89499761.59474.436469772.86575.056829784.76173.84219
9792.01571.214699796.50167.969629808.24261.846859847.39460.543239881.20362.20933
9893.87961.552079919.229 62.4805 9944.5860.613399957.25655.401949969.59147.87373
9981.28936.288169992.98830.4343110004.6531.1991910016.3437.0380410040.1855.58467
10051.7563.7310810063.8169.8096310075.8671.3291310136.1271.8594110164.8973.63377
10200.8974.2082110220.1875.8432910239.4780.1146210258.7683.3134410289.3886.86317
#Mann= 3 , 0 , 0
9731.974    0.12       09731.974    0.12       010289.38    0.12       0
#XS Ineff= 2 , 0
       0                               0
Bank Sta=9731.974,10289.38
Exp/Cntr=0.3,0.1

Type RM Length L Ch R = 1 ,6743.328,98.493100,98.493100,98.493100
XS GIS Cut Line= 6
801690.989461536 844527.26999106801739.728893573844486.693646608
801788.115105789844458.006913779801888.910093638844413.109426807
801937.166182872844387.181542753801994.395492784844346.822293487
#Sta/Elev= 30
9819.94287.506239838.98680.797359864.582 68.69519870.12367.63351 9889.5668.31166
9901.186 65.63869906.36264.985549936.06266.20855 9947.2462.158989958.21754.98378
9969.19345.773329980.16937.848929995.48930.0421710002.0727.4697410012.9927.45247
10023.9131.4246110034.8437.6074310045.7644.6763110068.2950.8506410079.6557.57453
   1009163.3033910102.3572.6544310108.8178.7127610114.1682.4684710127.1386.14467
10136.8390.4402210144.6694.58207 10150.696.9072710163.12100.947510174.88103.4792
#Mann= 3 , 0 , 0
9819.942    0.04       09819.942    0.04       010174.88    0.04       0
#XS Ineff= 2 , 0
       0                               0
Bank Sta=9819.942,10174.88
Exp/Cntr=0.3,0.1

Type RM Length L Ch R = 1 ,6644.834,98.493100,98.493100,98.493100
XS GIS Cut Line= 6
801831.429911681844569.671367549801852.152988256844551.250461621
801894.007711037844517.232055421801951.524127075844471.001574307
802002.592680148844426.991653341802039.855350692844391.619890569
#Sta/Elev= 30
9917.33769.707779922.11469.532959924.36969.068469935.49463.191919948.73352.11796
9961.61942.551699970.82935.067969974.50632.769699987.39227.38397    999928.36062
10000.2628.6498710013.0832.9221110018.5534.9664310025.9236.8747210038.7540.98982
10051.5943.6141510064.4246.8626110077.3848.8654810090.5853.26158 10097.3 56.4763
10103.7860.7226210112.6265.6847910116.9868.5262710130.19 77.566510143.53 86.2655
10157.6396.9244310172.15107.240310184.89114.970410186.68115.761510191.59 117.436
#Mann= 3 , 0 , 0
9917.337    0.04       09917.337    0.04       010191.59    0.04       0
#XS Ineff= 2 , 0
       0                               0
Bank Sta=9917.337,10191.59
Exp/Cntr=0.3,0.1

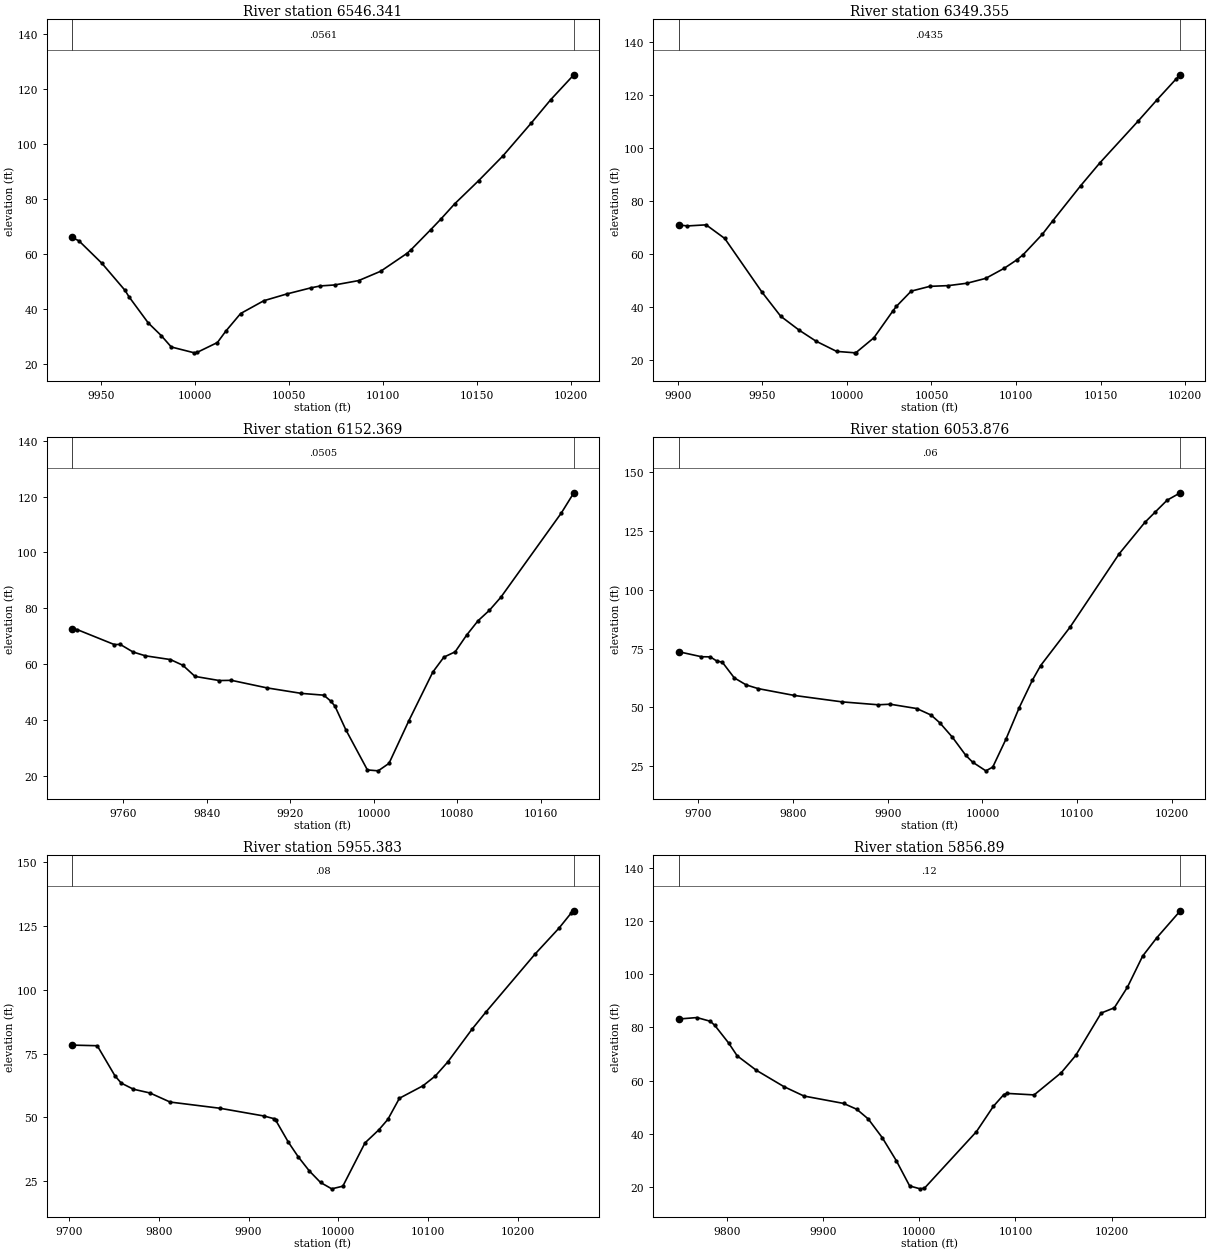
Type RM Length L Ch R = 1 ,6546.341,196.986200,196.986200,196.986200
XS GIS Cut Line= 5
801927.410920987844637.987262408801964.910224803844585.490603707
801966.030280074844583.833655854801997.643344588844540.133434392
802089.141120447844425.377267111
#Sta/Elev= 30
9934.48666.170819938.15764.907079950.44656.703659962.73546.875859964.74644.63927
9975.02435.10614 9981.95 30.49669987.31426.339239999.59224.20887   1000124.35076
 10011.927.96549 10016.3 32.052410024.2538.5001410036.5943.1520710048.93 45.6267
 10061.547.8025710066.7448.5314210074.2948.8799410087.0850.4684610098.8253.86151
10112.6660.2811710114.8661.5869410125.4568.95904 10130.9 72.844210138.2478.37395
10151.0386.8266610163.8295.7150810179.02107.7445 10189.4116.2405 10201.7125.2787
#Mann= 3 , 0 , 0
9934.486  0.0561       09934.486  0.0561       0 10201.7  0.0561       0
#XS Ineff= 2 , 0
       0                               0
Bank Sta=9934.486,10201.7
Exp/Cntr=0.3,0.1

Type RM Length L Ch R = 1 ,6349.355,196.986200,196.986200,196.986200
XS GIS Cut Line= 5
802100.799570114844759.796952174 802142.28747879844670.369141409
802143.154269266  844668.5667335802183.253647281844581.831121035
802230.078594894844492.807181743
#Sta/Elev= 30
9900.41770.915149905.70570.532039916.72970.942969927.75365.79247  9949.845.49084
9960.824 36.42669971.84831.113259981.68427.017429993.89523.1393710004.9322.59342
 10005.422.7049910015.9528.2892210026.9638.2314510029.2340.1430110037.9845.90109
   10049 47.707110060.0147.9900110071.0348.8933110082.0550.7199510093.0754.56039
10100.31 57.652310104.2759.7111610115.5767.3910410121.7972.5320810138.1785.69605
10149.4794.2849210172.07110.055710183.37 118.19310194.67126.062110197.14127.6286
#Mann= 3 , 0 , 0
9900.417  0.0435       09900.417  0.0435       010197.14  0.0435       0
#XS Ineff= 2 , 0
       0                               0
Bank Sta=9900.417,10197.14
Exp/Cntr=0.3,0.1

Type RM Length L Ch R = 1 ,6152.369,98.493100,98.493100,98.493100
XS GIS Cut Line= 6
802192.071367259844993.066640343802249.087730835 844908.70691106
802301.071981424844815.005489611 802316.19148318844775.702804988
802347.398171023844671.173099929802400.640926763844563.171180042
#Sta/Elev= 30
9711.00372.711289715.98572.382929751.40667.047189757.18767.080189769.42664.37516
9781.22863.01191 9805.2761.663779817.152 59.62329828.79955.636169852.09354.15801
 9863.7454.230829897.65751.536979930.776 49.55939952.20548.923619958.84846.81355
9962.89544.989859973.25736.586539993.98222.1714410004.3221.8448610014.6724.51249
10033.5539.6581710056.6957.2031610067.2762.5347810078.08 64.439810089.0270.39245
10099.9775.5428910110.9179.3030610121.8583.9657210179.77114.100310191.81121.3544
#Mann= 3 , 0 , 0
9711.003  0.0505       09711.003  0.0505       010191.81  0.0505       0
#XS Ineff= 2 , 0
       0                               0
Bank Sta=9711.003,10191.81
Exp/Cntr=0.3,0.1

Type RM Length L Ch R = 1 ,6053.876,98.493100,98.493100,98.493100
XS GIS Cut Line= 6
802210.135858467845031.453684138802357.991656973 844841.22630567
802390.040730624844804.802548731 802450.02025749844744.321263436
802510.295806289844672.793346539802547.857017312844623.903890667
#Sta/Elev= 30
9679.11173.676179703.33271.533359712.61671.483729719.62769.672349725.28169.24146
9737.94762.552129750.61259.532199763.27857.969839801.27455.070689851.93652.32983
9889.93251.099429902.59751.335819930.65249.49936 9945.7946.721989954.976 43.4303
9968.29637.288349982.50929.539529989.58326.71029 10003.6  23.00110010.8824.60031
10024.8536.5073410038.8249.85751 10052.861.6088810061.4767.7906210092.5184.12227
 10144.4 115.33110171.42128.643910182.33133.046310194.94138.103510208.93  141.27
#Mann= 3 , 0 , 0
9679.111    0.06       09679.111    0.06       010208.93    0.06       0
#XS Ineff= 2 , 0
       0                               0
Bank Sta=9679.111,10208.93
Exp/Cntr=0.3,0.1

Type RM Length L Ch R = 1 ,5955.383,98.493100,98.493100,98.493100
XS GIS Cut Line= 6
802257.097460022845066.148602792802352.310812078844961.117345945
802387.394682615844927.229025728802539.289435518844808.843537016
802583.952108138844766.887844582802661.764210757844682.704150951
#Sta/Elev= 30
9703.34978.327219731.42378.087359751.17966.279359758.14663.448599771.76261.05169
9790.14959.582189812.609 56.03079868.32553.591349917.10250.57223 9928.0449.55071
9930.27948.923719944.30640.359729955.35934.595049967.80229.028759980.24624.53543
9992.689 22.047810005.0723.0851710029.7840.0420310045.21 45.154410055.2449.24266
10068.1457.5158110094.4262.4070610108.1466.2397810121.8671.6649110149.3884.71333
10164.3191.1900610219.31113.993210246.07124.172510259.45130.010110262.52130.9257
#Mann= 3 , 0 , 0
9703.349    0.08       09703.349    0.08       010262.52    0.08       0
#XS Ineff= 2 , 0
       0                               0
Bank Sta=9703.349,10262.52
Exp/Cntr=0.3,0.1

Type RM Length L Ch R = 1 , 5856.89,98.493100,98.493100,98.493100
XS GIS Cut Line= 6
802351.343681385845111.266474718802429.537162201845035.264937049
802532.956983728844938.094050984802565.176501524844907.286042578
802647.714443704844824.385720788802721.599382513844744.728414357
#Sta/Elev= 30
9750.04983.096619769.10883.647319783.05182.255489787.72280.705289802.07274.09746
9810.93769.287229830.77263.874259859.47957.715039880.312  54.1779921.48351.40346
9935.20649.196219947.08945.565939961.69138.519399976.29229.85818  9990.120.40785
   1000119.3237910005.4819.57358 10059.540.8256810077.0350.3123710087.8554.71719
10091.1455.1710310119.3654.5996510147.5862.9541610162.56 69.419210189.0185.34513
10202.6587.3159810216.2995.0692710232.07106.741410246.77113.626810271.21123.7536
#Mann= 3 , 0 , 0
9750.049    0.12       09750.049    0.12       010271.21    0.12       0
#XS Ineff= 2 , 0
       0                               0
Bank Sta=9750.049,10271.21
Exp/Cntr=0.3,0.1

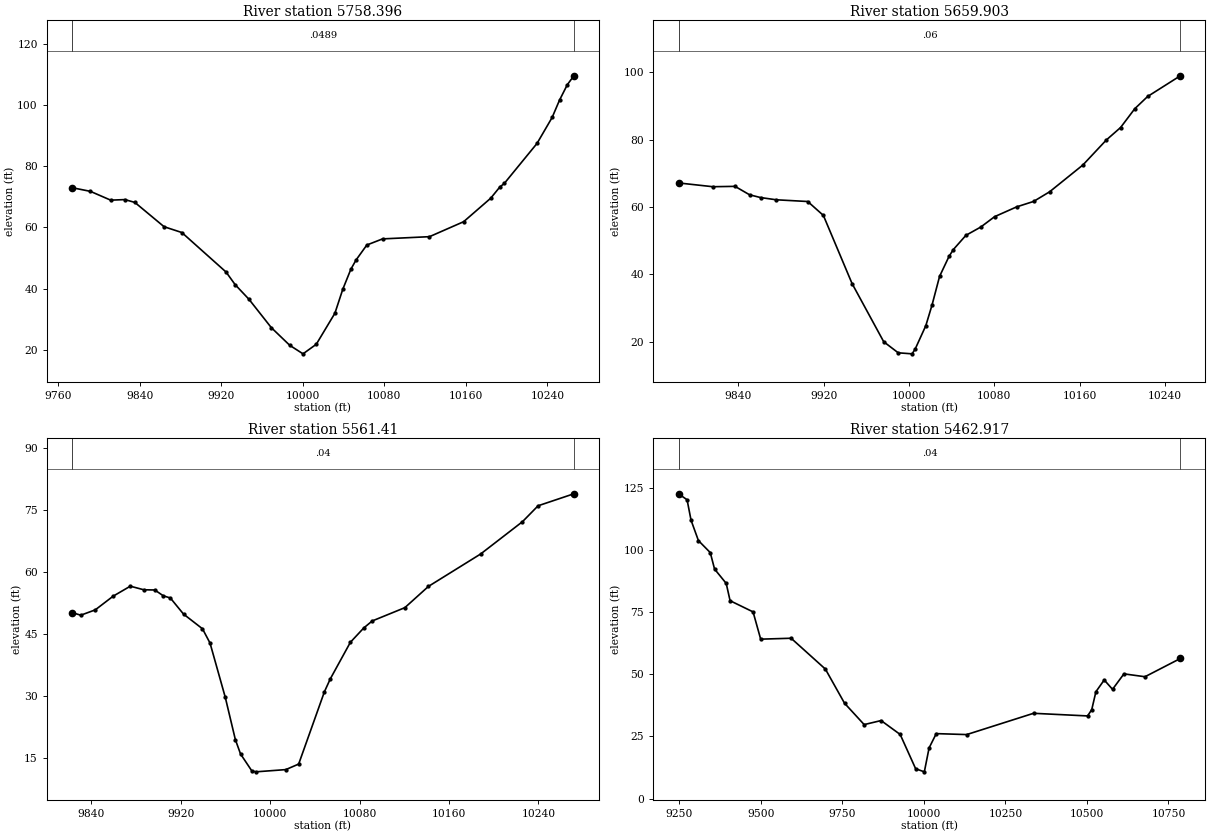
Type RM Length L Ch R = 1 ,5758.396,98.493100,98.493100,98.493100
XS GIS Cut Line= 6
802447.119131515845167.175084088802533.907674554845084.161896203
802582.631518283845031.681657448802660.522654349844938.172468338
802730.391566367844858.324085371802779.345020984844804.586698139
#Sta/Elev= 30
9773.78972.974459791.775 71.77559811.66668.899979825.59969.083329835.39168.15706
9864.04460.217029881.45858.321069924.89845.39159 9933.6941.309389947.33536.49502
9969.19227.251119987.29321.4619510000.3318.6727510013.3321.7963610031.6231.95223
10039.3339.7688110047.2746.3291810052.3349.3317410062.9254.2396610078.3356.23679
10124.38 56.964810157.8661.8528310184.4469.5348210193.3173.1689710197.8174.38394
10229.8587.43474 10244.795.9295310251.92101.573510259.55106.6136   10266109.5485
#Mann= 3 , 0 , 0
9773.789  0.0489       09773.789  0.0489       0   10266  0.0489       0
#XS Ineff= 2 , 0
       0                               0
Bank Sta=9773.789,10266
Exp/Cntr=0.3,0.1

Type RM Length L Ch R = 1 ,5659.903,98.493100,98.493100,98.493100
XS GIS Cut Line= 6
802525.046149695845215.945734925802559.678643622845186.175279018
802636.004373145845115.506420615802671.603349036845078.925919112
802765.263807576 844964.04005052802845.546061835844873.209728289
#Sta/Elev= 30
9784.06667.110139816.19865.990249836.98766.096049850.61563.595679860.90362.77474
9875.62262.109719905.12861.596919919.77957.471829946.65137.248699976.32119.96486
9989.912 16.6794 10002.9 16.373410005.8117.7948810015.7824.7333410021.6630.92629
10028.67 39.371910037.5145.2905310041.5647.3317910053.3651.5574510067.3454.03112
10080.2357.0959810100.9160.0071210116.7661.6190610131.7964.4838310162.9572.43957
10184.9679.8729310198.2683.5619610211.56 89.138710223.6192.7752110254.2698.92538
#Mann= 3 , 0 , 0
9784.066    0.06       09784.066    0.06       010254.26    0.06       0
#XS Ineff= 2 , 0
       0                               0
Bank Sta=9784.066,10254.26
Exp/Cntr=0.3,0.1

Type RM Length L Ch R = 1 , 5561.41,98.493100,98.493100,98.493100
XS GIS Cut Line= 6
802608.784142367845268.353186125802657.966445262845227.137840247
802743.119589913 845138.60126936802794.113777988845055.041883327
802827.202419712845012.777572532802902.360085123844932.102313405
#Sta/Elev= 30
9822.74550.12751 9830.5449.499399843.494 50.78629859.50154.100629874.85856.51969
9886.93255.65092 9896.7455.600879904.34854.198589910.68553.66204 9922.4649.76845
9939.44146.206099946.17542.755799959.82229.62842 9968.8319.40218 9973.4715.91815
9983.52511.832579987.11711.5845510013.9612.1236210025.49 13.465310048.5530.97846
10053.7734.0728810071.77 42.943810083.7846.42172 10091.348.1020310120.5151.32427
10141.6356.4732710188.2964.3087910225.7572.1314110239.7275.9829610271.7278.88687
#Mann= 3 , 0 , 0
9822.745    0.04       09822.745    0.04       010271.72    0.04       0
#XS Ineff= 2 , 0
       0                               0
Bank Sta=9822.745,10271.72
Exp/Cntr=0.3,0.1

Type RM Length L Ch R = 1 ,5462.917,168.395200,168.395200,168.395200
XS GIS Cut Line= 6
802213.425386706 845589.60131866802629.407732861845330.139754799
802742.298178034845249.989739538802815.772337856845163.895102367
 802929.64612333 845071.19593992803332.216847688844561.911716431
#Sta/Elev= 30
9247.733122.68459273.946 120.2699286.096112.04819308.651103.8509 9345.0299.00448
 9358.1992.381129393.89986.606019405.80279.638219476.284 75.13489499.621 64.1594
9592.96764.529169697.983 52.11299756.71138.372119816.90329.765429868.79131.39146
9927.33125.795019974.76211.9908510001.4210.7481910015.9720.3711410037.9526.13291
10131.2325.7460410336.2434.3125610501.9533.25407 10514.735.7832810527.45  42.991
10552.9447.7351310578.4343.9679810613.4250.1909310677.9349.0321410786.3256.37507
#Mann= 3 , 0 , 0
9247.733    0.04       09247.733    0.04       010786.32    0.04       0
#XS Ineff= 2 , 0
       0                               0
Bank Sta=9247.733,10786.32
Exp/Cntr=0.3,0.1