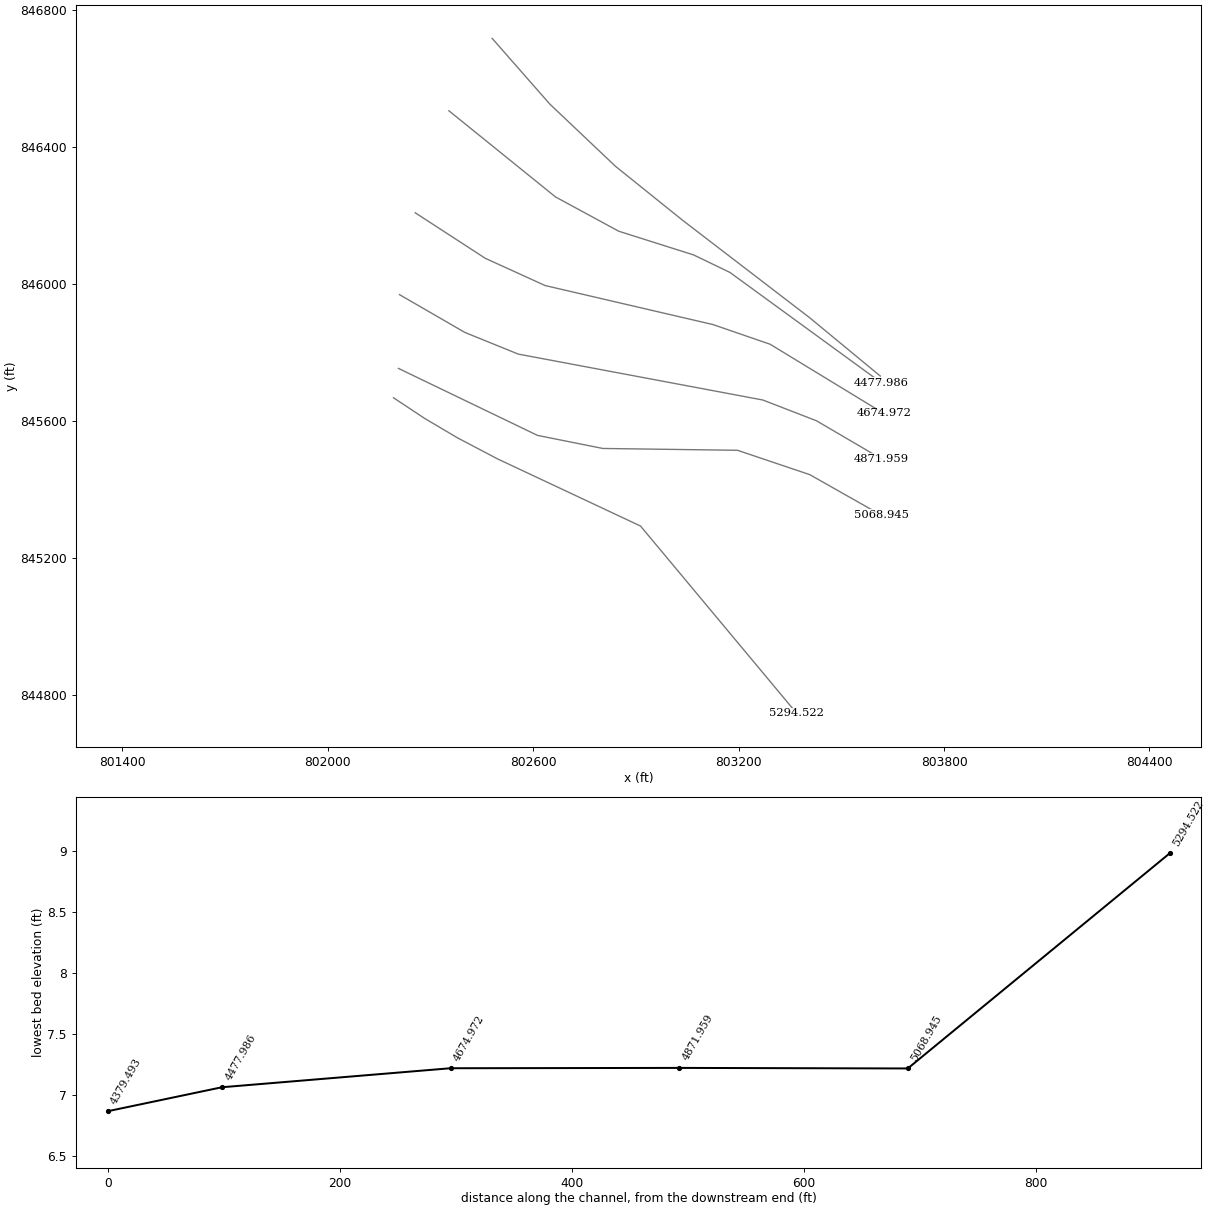
HEC-RAS study 18261_ras.prj: 18261

--- 18261_ras.g01 (geometry) --- (continued)

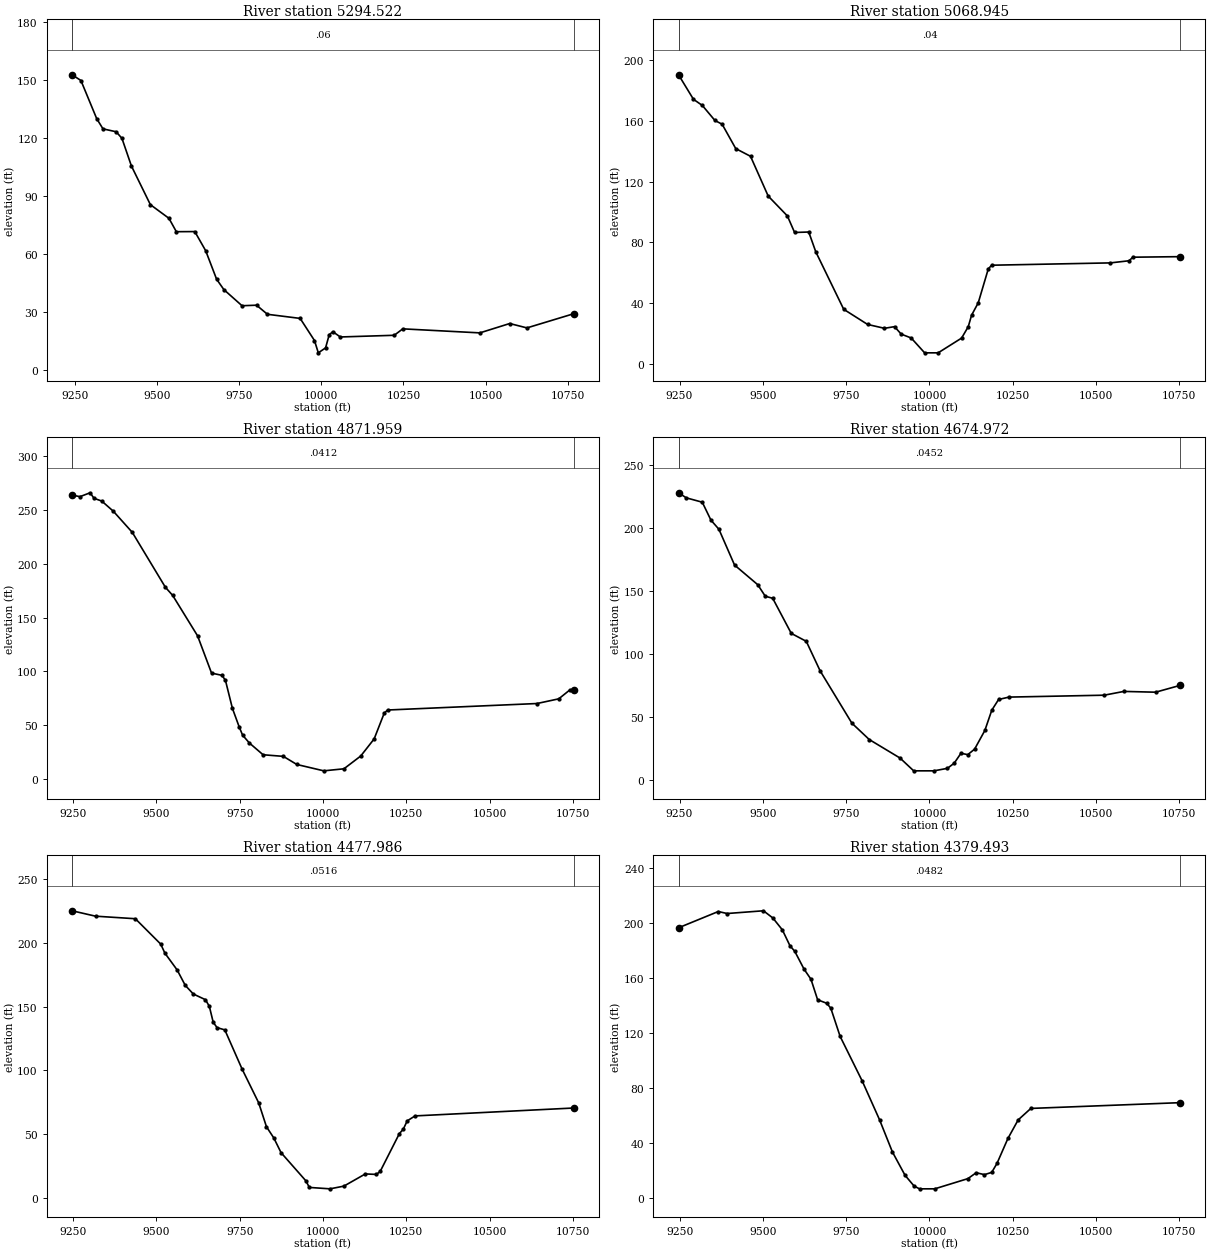
Type RM Length L Ch R = 1 ,5294.522,225.577200,225.577200,225.577200
XS GIS Cut Line= 6
802192.535780252845666.919221755802283.698536178845606.555142589
802379.671366999845549.796232013802496.618002512845488.334862759
802913.789788604845292.444204763803369.943877578844745.402271003
#Sta/Elev= 30
9242.416152.50619269.359149.54899317.333129.85779336.457124.58729376.501123.0944
9394.097119.68979422.972105.4017 9480.5785.468819537.05478.414829559.54471.51112
9615.67571.566689648.81761.68097 9681.9646.987499704.05541.621959759.29333.29277
9803.48433.567659836.62728.870669936.05526.751559979.64715.339099991.2938.976897
10013.3911.5388810024.4418.3089110035.4819.8987510058.1317.1674510222.1818.03564
10248.2221.3613310482.5919.2797610573.4224.1059310625.8121.8499710768.5129.18979
#Mann= 3 , 0 , 0
9242.416    0.06       09242.416    0.06       010768.51    0.06       0
#XS Ineff= 2 , 0
       0                10043.92       0
Bank Sta=9242.416,10768.51
Exp/Cntr=0.3,0.1

Type RM Length L Ch R = 1 ,5068.945,196.986200,196.986200,196.986200
XS GIS Cut Line= 6
802206.943965975845752.695867083802613.016592516845557.104628128
802803.661806404845518.971492224803196.947781129845513.610485669
803408.070897275845442.474978828803616.448480272845324.480565823
#Sta/Elev= 30
 9246.97  190.559291.739174.3765 9318.54170.29989356.235  160.419377.839157.9453
9418.731141.86079463.009 136.8119516.094110.58099573.61497.490649595.31686.57192
9637.76186.879399658.92773.824869742.741 35.92259814.47525.931029865.08423.39047
9895.268 24.48429915.28919.558259945.30317.005669985.663 7.2142510026.157.214139
10096.53  16.93610116.5324.4484810126.5432.0257510146.5640.20868 10176.762.57735
10186.7564.9867510543.1466.5209910599.2467.9267110610.5570.2724410753.0770.63422
#Mann= 3 , 0 , 0
 9246.97    0.04       0 9246.97    0.04       010753.07    0.04       0
#XS Ineff= 2 , 0
       0                               0
Bank Sta=9246.97,10753.07
Exp/Cntr=0.3,0.1

Type RM Length L Ch R = 1 ,4871.959,196.986200,196.986200,196.986200
XS GIS Cut Line= 6
802209.805926236 845968.24096166802400.809551144845857.776376524
802556.778312862845794.509037122803270.838938882845660.440437723
803427.755979304845599.704328337803618.091505668845488.159111857
#Sta/Elev= 30
9246.913263.98499270.745262.59879301.012266.18979312.709261.06099336.103258.4676
9370.843248.98469427.688229.31589526.956178.21299548.799170.64189623.622132.9553
9665.59198.231529696.87296.174879707.29991.475439728.12165.491029748.59548.08582
9758.83240.418099779.30733.092589820.25622.197349881.05520.697739921.511 13.1447
10002.427.21868810062.929.11387410113.3321.0146810153.6636.95989 10183.960.97416
10193.9963.8686310642.3869.9107710707.7174.2737610740.9482.5484210753.0982.32248
#Mann= 3 , 0 , 0
9246.913  0.0412       09246.913  0.0412       010753.09  0.0412       0
#XS Ineff= 2 , 0
       0                               0
Bank Sta=9246.913,10753.09
Exp/Cntr=0.3,0.1

Type RM Length L Ch R = 1 ,4674.972,196.986200,196.986200,196.986200
XS GIS Cut Line= 6
802256.004701307846207.070710671 802460.39356796 846074.29830212
802635.043260271845994.709552371803125.416798569845880.727854325
  803292.2664104845823.244754877803623.923052393845621.240467463
#Sta/Elev= 30
9246.939228.01699270.478223.97229318.175220.53429344.136206.32319368.142199.0381
9415.069170.63359484.643155.02699507.233145.8835  9529.6144.23019585.323116.3627
9630.387110.05599672.04886.546769767.28645.052649819.27432.099429911.86617.35521
9952.705 7.2196810013.527.21597810054.079.20517610074.3513.3058310094.6321.17148
10115.0920.0777210135.5724.4452810166.2939.24886 10187.255.4035710207.6363.88624
10238.9465.7754310524.5367.2845510583.6170.2823510678.8469.6640910753.04 75.1316
#Mann= 3 , 0 , 0
9246.939  0.0452       09246.939  0.0452       010753.04  0.0452       0
#XS Ineff= 2 , 0
       0                               0
Bank Sta=9246.939,10753.04
Exp/Cntr=0.3,0.1

Type RM Length L Ch R = 1 ,4477.986,98.493100,98.493100,98.493100
XS GIS Cut Line= 6
802354.173969767846505.031699737 802665.72728083846253.325132409
 802850.22839355846153.261768257803068.852877244846084.063764566
803174.992034896846032.875356961803616.883115598845710.929126651
#Sta/Elev= 30
9246.935 225.273 9317.39221.03379436.863219.03699512.946199.14659525.627191.9893
9562.317178.84729586.594166.76329610.871159.96169647.287155.49539658.941150.2899
9670.558137.79239682.175133.56149705.409131.80529757.173101.09899807.11674.53312
9830.44355.757699852.476 46.98599874.20635.454439948.74313.339059959.1038.168154
10021.157.06018710062.759.18476310127.1718.7607910160.5518.3726410171.8720.77777
10229.3350.39749 10241.153.8804710252.8660.40153 10276.464.2959710753.0770.50206
#Mann= 3 , 0 , 0
9246.935  0.0516       09246.935  0.0516       010753.07  0.0516       0
#XS Ineff= 2 , 0
       0                               0
Bank Sta=9246.935,10753.07
Exp/Cntr=0.3,0.1

Type RM Length L Ch R = 1 ,4379.493,0.000000,0.000000,0.000000
XS GIS Cut Line= 6
802480.456383671846716.514995296802648.915176869846524.552994752
 802840.63052681846342.902846665803038.075101638846184.165229391
 803406.28526667845901.805739167803613.863424565845730.463900877
#Sta/Elev= 30
9246.883196.38399366.173208.1913 9392.75206.74969501.754208.7361 9530.09203.4797
9558.449194.91499581.472183.29029595.577179.39859623.787166.30969644.396159.0367
9664.393144.11559691.404141.61879703.907138.05919731.922 117.545 9798.2685.14309
9850.32956.979229888.77733.693179926.887 16.66359953.9948.8859049970.2096.863503
10015.976.869679 10115.514.2817110140.3518.5558510165.2117.1751510186.9518.80163
10202.8325.3338410235.59 43.431810266.3556.9061810304.4665.2470910753.1469.43433
#Mann= 3 , 0 , 0
9246.883  0.0482       09246.883  0.0482       010753.14  0.0482       0
#XS Ineff= 2 , 0
       0                               0
Bank Sta=9246.883,10753.14
Exp/Cntr=0.3,0.1